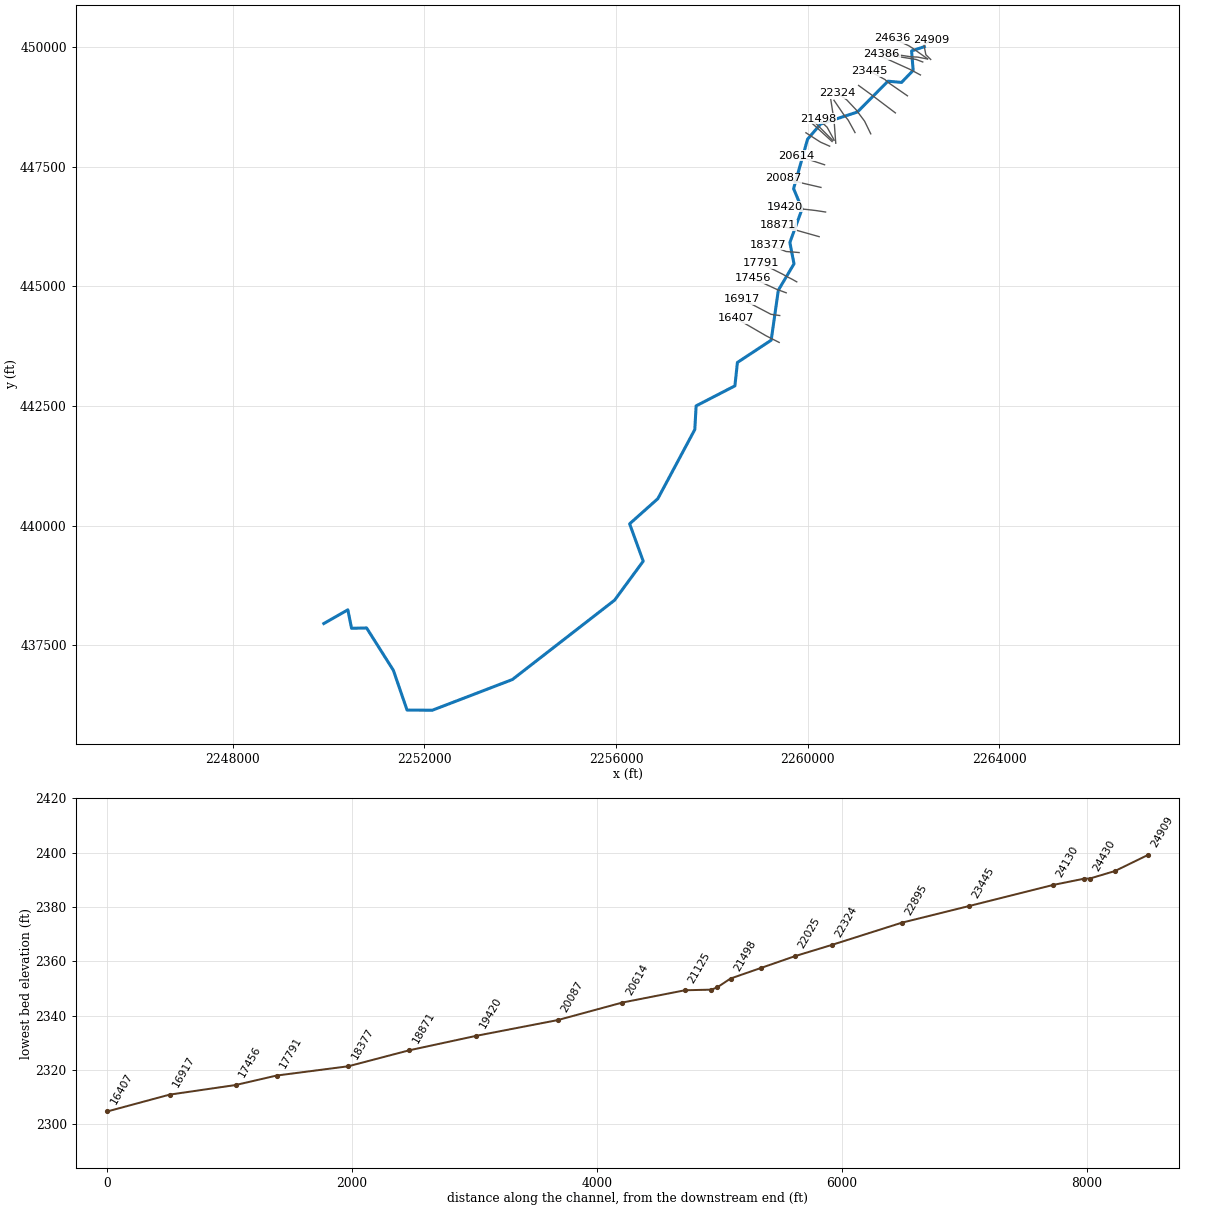
--- BRWNSCK.prj (project) ---

Proj Title=BRWNSCK
Current Plan=p01
Default Exp/Contr=0,0
English Units
Geom File=g01
Flow File=f01
Plan File=p01
Background Map Layer=FWY
Background Map Layer=Inundation Boundary (01pct Value_0)
Background Map Layer=Google Satellite
Background Map Layer=FWY
Background Map Layer=Inundation Boundary (01pct Value_0)
BEGIN DESCRIPTION:
----------MODEL BY WOOD PLC 2021----------
Stream Name: Brown Creek Lower Reach
Flood Zone: Detail (XS 1504-21538) and  Enhanced Approximate (XS 21538- 24994)
Pocahontas County, WV
HEC-RAS Version: RAS 6.1
Vertical Datum: NAVD88
Projection: NAD 1983 StatePlane West Virginia S FIPS 4702 (US Feet)
Terrain: 1-meter LIDAR (FEMA Region III 3DEP collected 2016-2018)
Land Use: 2019 NLCD
Hydrologic Method:
WV SIR2010-5033 regression equations
Model Notes:
channel burning applied based on survey
Zone AE - 0-21786
Zone A- 21786-25445
END DESCRIPTION:
DSS File=dss
DSS Export Rating Curves= 0
DSS Export Rating Curve Sorted= 0
DSS Export Volume Flow Curves= 0
DXF OffsetX= 0
DXF OffsetY= 0
DXF ScaleX= 0
DXF ScaleY= 0

--- BRWNSCK.p01 (plan) ---

Plan Title=Floodplain
Program Version=6.10
Short Identifier=Floodplain
Geom File=g01
Flow File=f01
Subcritical Flow
K Sum by GR= 0
Std Step Tol= 0.01
Critical Tol= 0.01
Num of Std Step Trials= 20
Max Error Tol= 0.3
Flow Tol Ratio= 0.001
Split Flow NTrial= 30
Split Flow Tol= 0.02
Split Flow Ratio= 0.02
Log Output Level= 0
Friction Slope Method= 1
Unsteady Friction Slope Method= 2
Unsteady Bridges Friction Slope Method= 1
Parabolic Critical Depth
Global Vel Dist= 0 , 0 , 0
Global Log Level= 0
CheckData=True
Encroach Param=-1 ,0,0, 2
Encroach River=BRWNSCK
Encroach Reach=Main
Encroach Node=21747
       1  399.83   475.6
Encroach Node=21498
       1   415.8   439.9
Encroach Node=21389
       1   409.9   438.2
Encroach Node=21341
       1  412.55   440.5
Encroach Node=21125
       1   456.3   477.8
Encroach Node=20614
       1  419.32  501.04
Encroach Node=20087
       1  542.81  574.78
Encroach Node=19420
       1   492.3   565.7
Encroach Node=18871
       1   488.4  564.18
Encroach Node=18377
       1  120.62  200.83
Encroach Node=17791
       1  201.22     255
Encroach Node=17456
       1  128.38  208.95
Encroach Node=16917
       1  110.33  204.31
Encroach Node=16407
       1   156.2  273.21
Encroach Node=16094
       1   319.1  389.93
Encroach Node=15768
       1  325.04   375.2
Encroach Node=15541
       1  295.24   494.2
Encroach Node=15267
       1  254.29  402.15
Encroach Node=14980
       1   283.1  411.28
Encroach Node=14689
       1   211.6  308.59
Encroach Node=14481
       1  278.21  339.28
Encroach Node=14149
       1  237.78  295.04
Encroach Node=13815
       1  453.94   532.9
Encroach Node=13410
       1  413.08   464.2
Encroach Node=13079
       1  469.84   540.5
Encroach Node=12550
       1  353.85  407.38
Encroach Node=12042
       1   378.5  436.06
Encroach Node=11694
       1  259.33  350.15
Encroach Node=11383
       1   223.8  345.02
Encroach Node=11000
       1     380  480.01
Encroach Node=10602
       1  338.48   532.6
Encroach Node=9994
       1   97.81  184.84
Encroach Node=9596
       1    62.8   106.1
Encroach Node=9079
       1      77     118
Encroach Node=8552
       1  295.98  356.99
Encroach Node=7967
       1   195.4  306.64
Encroach Node=7630
       1   321.9  437.97
Encroach Node=7386
       1   391.1  580.82
Encroach Node=7342
       1  397.52  585.63
Encroach Node=6919
       1     223  359.92
Encroach Node=6511
       1     169  366.25
Encroach Node=6229
       1  241.51  330.93
Encroach Node=6071
       1     183     265
Encroach Node=5886
       1  234.34  381.96
Encroach Node=5851
       1  251.46     388
Encroach Node=5779
       1   231.5  315.74
Encroach Node=5749
       1     222  307.89
Encroach Node=5457
       1  132.73  229.65
Encroach Node=4953
       1     258  380.82
Encroach Node=4576
       1     702  775.15
Encroach Node=4164
       1 1840.18    1976
Encroach Node=4084
       1    1798 1868.06
Encroach Node=3213
       1  1133.8 1278.33
Encroach Node=2692
       1 1143.43  1197.1
Encroach Node=2226
       1 1728.81    2090
Encroach Node=1504
       1 1564.66  2041.3
Encroach Node=806
       1  1684.7 2008.85
Computation Interval=0.1SEC
Output Interval=1SEC
Instantaneous Interval=Max Profile
Mapping Interval=1HOUR
Computation Time Step Use Courant=        0
Computation Time Step Use Time Series=    0
Computation Time Step Count To Double=0
Computation Time Step Max Doubling=0
Computation Time Step Max Halving=0
Computation Time Step Residence Courant=0
Run HTab= 0
Run UNet= 0
Run Sediment= 0
Run PostProcess= 0
Run WQNet= 0
Run RASMapper=-1
UNET Theta= 0
UNET Theta Warmup= 0
UNET ZTol= 0
UNET ZSATol= 0
UNET MxIter= 0
UNET Max Iter WO Improvement= 0
UNET MaxInSteps= 0
UNET DtIC= 0
UNET DtMin= 0
UNET MaxCRTS= 0
UNET WFStab= 0
UNET SFStab= 0
UNET WFX= 1
UNET SFX= 1
UNET Gravity=32.174
UNET 1D Methodology=Finite Difference
UNET DSS MLevel= 1
UNET Pardiso=0
UNET DZMax Abort= 0
UNET Use Existing IB Tables= 0
UNET Froude Reduction=False
UNET Froude Limit= 0
UNET Froude Power= 0
UNET D1 Cores= 0
UNET WindReference=Eulerian
UNET WindDragFormulation=Hsu (1988)
UNET D2 Coriolis=0
UNET D2 Cores= 0
UNET D2 Theta= 1
UNET D2 Theta Warmup= 1
UNET D2 Z Tol= 0.01
UNET D2 Volume Tol= 0.01
UNET D2 Max Iterations= 20
UNET D2 Equation= 0
UNET D2 RampUpFraction=0.1
UNET D2 TimeSlices= 1
UNET D2 Turbulence Formulation=Non-Conservative (original)
UNET D2 Eddy Viscosity=0.3
UNET D2 Transverse Eddy Viscosity=0.1
UNET D2 Smagorinsky Mixing=0
UNET D2 BCVolumeCheck=0
UNET D2 Cores=0
UNET D2 SolverType=PARDISO (Direct)
UNET D2 Minimum Iterations= 2147483647
UNET D2 Maximum Iterations= 2147483647
UNET D2 Restart Number= 10
UNET D2 Relaxation Coeff=1.3
UNET D2 SOR Precondition Iterations= 10
UNET D2 ILUT Maximum Fill= 8
UNET D2 ILUT Tolerance=1E-08
UNET D1D2 MaxIter= 0
UNET D1D2 ZTol=0.01
UNET D1D2 QTol=0.1
UNET D1D2 MinQTol=1
DSS File=dss
Write IC File= 0
Write IC File at Fixed DateTime=0
Write IC File at Sim End=0
Echo Input=False
Echo Parameters=False
Echo Output=False
Write Detailed= 0
HDF Write Warmup=0
HDF Write Time Slices=0
HDF Flush=0
HDF Compression= 1
HDF Chunk Size= 1
HDF Spatial Parts= 1
HDF Use Max Rows=0
HDF Fixed Rows= 1
Calibration Method= 0
Calibration Iterations= 20
Calibration Max Change=0.05
Calibration Tolerance=0.2
Calibration Maximum=1.5
Calibration Minimum=0.5
Calibration Optimization Method= 1
WQ AD Non Conservative
WQ ULTIMATE=-1
WQ Max Comp Step=1HOUR
WQ Output Interval=15MIN
WQ Output Selected Increments= 0
WQ Output face flow=0
WQ Output face velocity=0
WQ Output face area=0
WQ Output face dispersion=0
WQ Output cell volume=0
WQ Output cell surface area=0
WQ Output cell continuity=0
WQ Output cumulative cell continuity=0
WQ Output face conc=0
WQ Output face dconc_dx=0
WQ Output face courant=0
WQ Output face peclet=0
WQ Output face adv mass=0
WQ Output face disp mass=0
WQ Output cell mass=0
WQ Output cell source sink temp=0
WQ Output nsm pathways=0
WQ Output nsm derived pathways=0
WQ Create Restart=0
WQ Fixed Restart=0
WQ System Summary=0
WQ Write To DSS=0
Sorting and Armoring Iterations= 10
XS Update Threshold= 0.02
Bed Roughness Predictor= 0
Hydraulics Update Threshold= 0.02
Energy Slope Method= 1
Volume Change Method= 1
Sediment Retention Method= 0
Sediment TS Multiplier= 1
Warm Up Method= 0
XS Weighting Method= 0
Number of US Weighted Cross Sections= 1
Number of DS Weighted Cross Sections= 1
Upstream XS Weight=0
Main XS Weight=1
Downstream XS Weight=0
Number of DS XS's Weighted with US Boundary= 1
Upstream Boundary Weight= 1
Weight of XSs Associated with US Boundary= 0
Number of US XS's Weighted with DS Boundary= 1
Downstream Boundary Weight= 0.5
Weight of XSs Associated with DS Boundary= 0.5
Percentile Method= 0
Sediment Output Level= 3
Mass or Volume Output= 0
Output Increment Type= 1
Profile and TS Output Increment= 1
Transport Output Increment 1
XS Output Flag= 0
XS Output Increment= 10
Read HDF5 Sediment Hotstart= 0
Sediment Hotstart Type= 0
Write Gradation File= 0
Read Gradation Hotstart= 0
Write HDF5 File= 1
Write Binary Output= 1
Write DSS Sediment File= 0
DSS Sediment Output Type= 1
SV Curve= 0
Specific Gage Flag= 0
Subcell Erosion Methods= 0
Subcell Deposition Methods= 0
Advection Scheme= 1
Matrix Solver= 0
Implicit Weighting Factor= 1
Maximum Outer Loop Convergence Iterations= 5
Convergence Maximum Absolute= 0.001
Convergence RMSE= 0.0001
Grain Fractions Max Abs Error= 0.001
Max Subgrid Regions= 1
Max Subgrid Length Scale= 3.402823E+38
Initial Layer Thickness= 3.402823E+38
Min Layer Thickness= 3.402823E+38
Max Layer Thickness= 3.402823E+38
Number of Layers= 5

--- BRWNSCK.f01 (steady flow) ---

Flow Title=Flow
Program Version=6.10
Number of Profiles= 7
Profile Names=01pct,FWY,10pct,04pct,02pct,0_2pct,01plus
River Rch & RM=BRWNSCK,Main            ,24909
     718     718     383     507     609     998    1060
River Rch & RM=BRWNSCK,Main            ,24636
     801     801     429     567     680    1110    1180
River Rch & RM=BRWNSCK,Main            ,22324
    1070    1070     578     760     909    1470    1580
River Rch & RM=BRWNSCK,Main            ,18377
    1330    1330     725     949    1130    1830    1960
River Rch & RM=BRWNSCK,Main            ,15267
    1510    1510     828    1080    1290    2070    2230
River Rch & RM=BRWNSCK,Main            ,12042
    1680    1680     926    1210    1440    2300    2480
River Rch & RM=BRWNSCK,Main            ,7967
    1880    1880    1040    1350    1610    2570    2780
Boundary for River Rch & Prof#=BRWNSCK,Main            , 1
Up Type= 0
Dn Type= 3
Dn Slope=0.005293
Boundary for River Rch & Prof#=BRWNSCK,Main            , 2
Up Type= 0
Dn Type= 3
Dn Slope=0.005293
Boundary for River Rch & Prof#=BRWNSCK,Main            , 3
Up Type= 0
Dn Type= 3
Dn Slope=0.005293
Boundary for River Rch & Prof#=BRWNSCK,Main            , 4
Up Type= 0
Dn Type= 3
Dn Slope=0.005293
Boundary for River Rch & Prof#=BRWNSCK,Main            , 5
Up Type= 0
Dn Type= 3
Dn Slope=0.005293
Boundary for River Rch & Prof#=BRWNSCK,Main            , 6
Up Type= 0
Dn Type= 3
Dn Slope=0.005293
DSS Import GetInterval= 0
DSS Import GetPeak= 0
DSS Import FillOption= 0

--- BRWNSCK.g01 (geometry) ---

Geom Title=Geometry
Program Version=6.10

River Reach=BRWNSCK         ,Main
Reach XY= 30
 2262438.0595505450002.6327310242262172.76116154  449914.9859799
  2262204.918485449508.1543344412261962.59963517 449256.46821776
2261678.30500005449281.8700000052261041.57700004448639.045000017
2260271.49964447448385.930834949       2260000.5448071.677000001
2259708.62900001447038.3199999932259885.67075239446614.679025412
2259631.07785079445914.6209428762259717.17000003445468.183000013
2259390.24300003444918.3770000192259240.68710078443874.122924432
2258535.66256702443409.2364813692258483.29107916 442920.67329888
2257673.55650485442503.2137864382257646.07300001442009.184000015
2256874.12573821440565.0078864522256284.98400003440039.852000013
2256568.86199999439259.8959999982255970.76599999438445.708000034
2253836.70700002436788.5349999962252166.58500002436148.205000013
2251637.59000002436150.7980000082251351.92900005436981.435000017
2250793.29799998437865.371000007     2250479.021437858.885000005
2250401.13800004      438243.7872249899.32300001437958.005999997

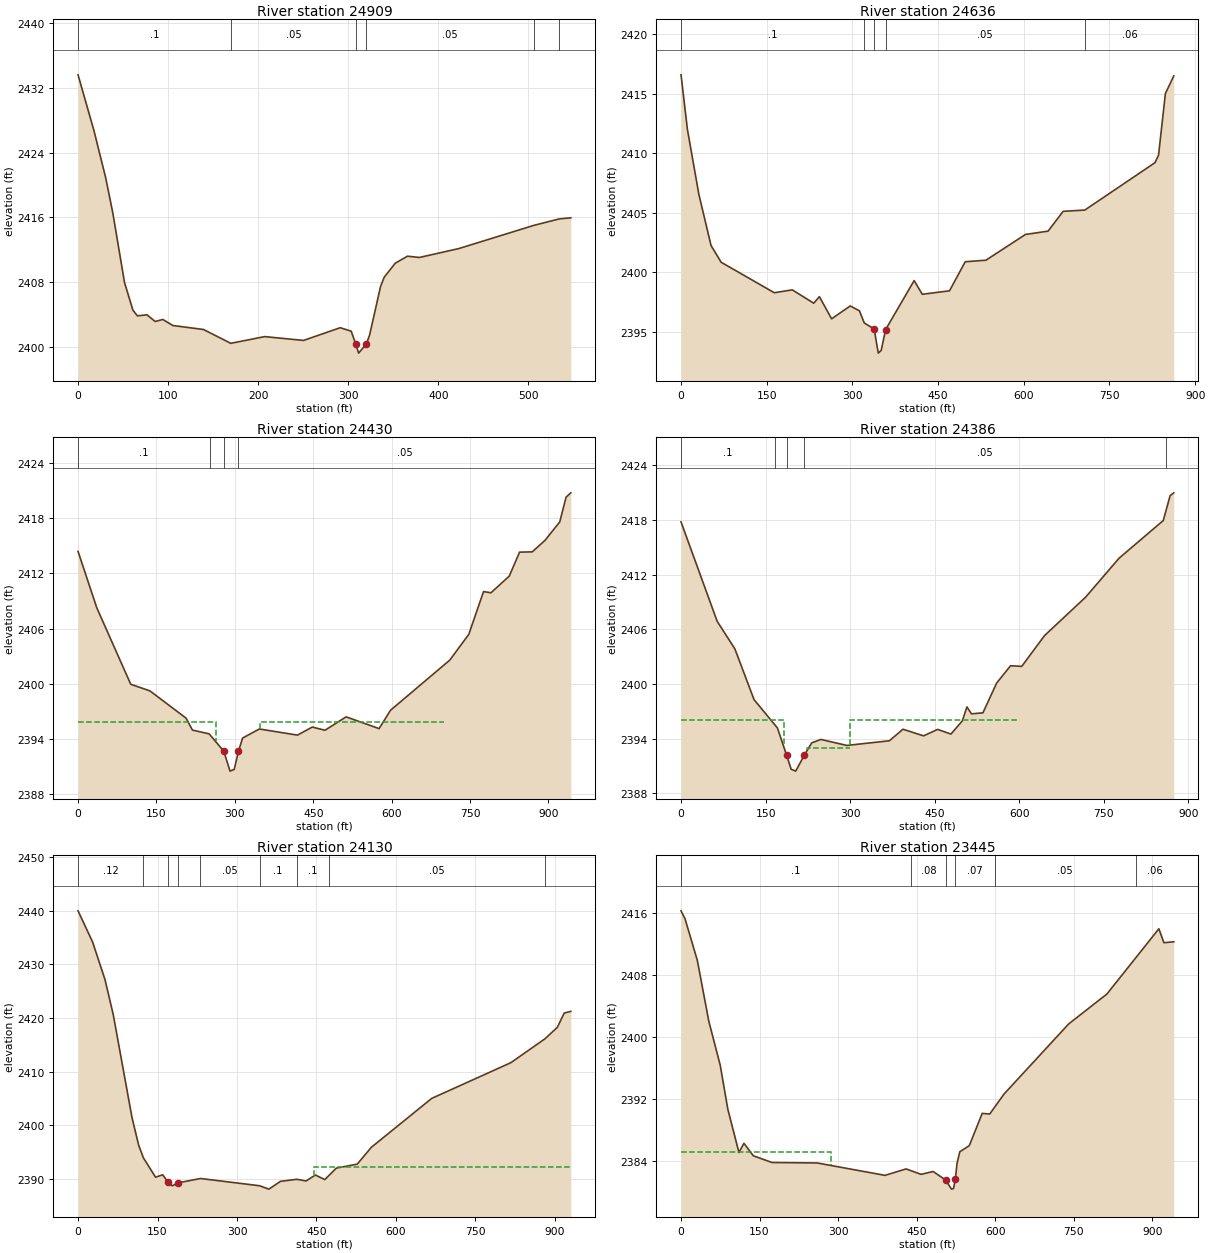
Type RM Length L Ch R = 1 ,24909   ,184.4,272.8,251.1
XS GIS Cut Line= 4
2262571.91758816449735.8922236172262469.96664443449834.632114006
2262430.63124094450041.745054823 2262590.3811449450152.526395259
#Sta/Elev= 30
       0 2433.61    17.7  2426.7    30.6 2420.93    38.6 2416.54    51.6 2407.94
    60.9 2404.54    65.8 2403.83    76.6 2403.95    85.6 2403.13    94.1 2403.38
   105.3 2402.63   139.3 2402.14   169.6 2400.43   207.2 2401.26   250.4 2400.79
   291.1 2402.36   303.3 2401.93  308.45 2400.32   311.5 2399.22   320.1 2400.34
   323.7 2401.44   335.9 2407.46     340 2408.61   352.2 2410.33   365.8  2411.2
     379 2411.04   422.8 2412.14   506.2 2415.01   534.5 2415.81  547.15 2415.94
#Mann= 6 ,-1,0
       0      .1       0   169.6     .05       0  308.45    .045       0
   320.1     .05       0   506.2     .06       0   534.5     .05       0
Bank Sta=308.45,320.1
XS Rating Curve= 0 ,0
Exp/Cntr=0.3,0.1

Type RM Length L Ch R = 1 ,24636   ,139.5,205.9,207.5
XS GIS Cut Line= 5
2262509.31809626449746.6696548482262225.80277472449948.918539073
2262219.94716614449953.8732847952262112.03275576450023.626354081
2261767.84138109 450180.28488674
#Sta/Elev= 30
       0 2416.59    11.2    2412    31.3 2406.54    52.5 2402.27    70.2 2400.86
   163.2  2398.3   194.8 2398.54   232.3 2397.42   242.2 2397.97   263.6 2396.11
   296.2 2397.19   312.3 2396.78   320.8 2395.76   338.1 2395.26   345.3 2393.23
   350.4 2393.46   358.2 2395.21   408.1 2399.32   422.3 2398.17     470 2398.46
   497.5  2400.9   533.8 2401.03   602.9 2403.19   642.5 2403.47   668.9 2405.13
   706.9 2405.24   829.8 2409.22   835.9 2409.85   847.9 2415.02862.5926  2416.5
#Mann= 5 ,-1,0
       0      .1       0   320.8     .05       0   338.1    .045       0
   358.2     .05       0   706.9     .06       0
Bank Sta=338.1,358.2
XS Rating Curve= 0 ,0
Exp/Cntr(USF)=0,0
Exp/Cntr=0.3,0.1

Type RM Length L Ch R = 1 ,24430   ,47,43.7,41.1
XS GIS Cut Line= 4
2262499.22382926449746.9218140952262291.39076065449786.300711307
2262164.50320296449790.6761443312261567.25659525449882.560237825
#Sta/Elev= 30
       0  2414.4    35.7 2408.28   100.8 2399.93   137.5 2399.21   206.7 2396.24
   218.8 2394.94   250.8 2394.53   278.8 2392.64   290.8 2390.47   298.8 2390.66
   306.8 2392.62   314.8 2394.07   346.9 2395.06   419.8 2394.39   448.1 2395.27
   472.4 2394.92   512.9 2396.38     576  2395.1   597.8  2397.1   711.2 2402.56
   747.6 2405.37   775.8 2410.03   789.9 2409.89     825 2411.71   844.7 2414.32
     869 2414.35   893.3  2415.6   921.6 2417.61   933.7 2420.31942.7671 2420.78
#Mann= 4 ,-1,0
       0      .1       0  251.53     .05       0   278.8    .045       0
   306.8     .05       0
#XS Ineff= 3 ,-1
       0     263  2395.8     321     348  2394.1     348     700  2395.8
Permanent Ineff=
       F       F       F
Bank Sta=278.8,306.8
XS Rating Curve= 0 ,0
Exp/Cntr(USF)=0,0
Exp/Cntr=0.3,0.1

Type RM Length L Ch R = 1 ,24386   ,257.9,255.9,250.1
XS GIS Cut Line= 4
2262405.15201926449683.4780352542262267.32587902449735.983231536
2262175.44178552449751.2972471192261549.75486315449849.744490148
#Sta/Elev= 30
       0  2417.8    64.1 2406.89    95.6 2403.85   129.5 2398.29     171 2395.18
   187.2  2392.2   195.3 2390.65   203.4 2390.44  218.64 2392.19   231.8 2393.54
     248 2393.92   294.1 2393.26   369.5 2393.77   393.8 2395.04   430.2 2394.31
   455.1 2395.02   478.8 2394.51     499 2395.96   507.1 2397.49   515.2 2396.73
   535.5 2396.84   559.8  2400.1   584.5 2402.01   604.3 2401.94   644.8 2405.32
   717.7 2409.54   776.9 2413.81   855.4 2417.95   867.5 2420.68874.0245 2420.99
#Mann= 5 ,-1,0
       0      .1       0  167.49     .05       0   187.2    .045       0
  218.64     .05       0  860.64     .06       0
#XS Ineff= 3 ,-1
       0     182    2396     224     300 2392.97     300     600    2396
Permanent Ineff=
       F       F       F
Bank Sta=187.2,218.64
XS Rating Curve= 0 ,0
Exp/Cntr(USF)=0,0
Exp/Cntr=0.3,0.1

Type RM Length L Ch R = 1 ,24130   ,677.5,684.9,668.1
XS GIS Cut Line= 3
  2262357.022256449412.2011877942262136.06288831 449530.33787943
2261516.93911548449810.365592937
#Sta/Elev= 30
       0 2439.98    27.5 2434.16    50.9 2427.15    66.4 2420.65   101.8 2401.47
   114.4 2396.29   123.4 2393.93   146.3 2390.33   159.7 2390.78   169.8 2389.43
   177.9 2388.72   188.7 2389.28   231.1 2390.09   342.6 2388.74   360.2 2388.11
   382.1 2389.56   412.9 2389.94   430.4 2389.63     448 2390.74   465.6 2389.89
   473.3 2390.63   487.5 2392.03     527 2392.77   553.4 2395.89   667.5 2405.02
   816.8 2411.67   881.4 2416.14   904.6 2418.26   917.7 2420.94 930.065 2421.24
#Mann= 9 ,-1,0
       0     .12       0   123.4      .1       0   169.8    .045       0
   188.7      .1       0   231.1     .05       0   342.6      .1       0
   412.9      .1       0   473.3     .05       0   881.4     .06       0
#XS Ineff= 2 , 0
                          445.07         2392.21
Permanent Ineff=
       F       F
Bank Sta=169.8,188.7
XS Rating Curve= 0 ,0
Exp/Cntr(USF)=0,0
Exp/Cntr=0.3,0.1

Type RM Length L Ch R = 1 ,23445   ,526.2,550.5,527.7
XS GIS Cut Line= 4
2262085.74540854448976.8456019522261696.33186944  449245.9347329
2261617.57407502449315.9416612762261300.35518081449490.958982218
#Sta/Elev= 30
       0 2416.32     7.6  2415.3    31.1 2409.93    53.1 2402.04    74.8 2396.39
    89.4 2390.68   110.6  2385.1   120.2 2386.28     138 2384.67   173.9  2383.8
   260.1 2383.74   389.5 2382.14   429.8 2382.97   458.5 2382.27   481.4 2382.64
   505.7 2381.52   516.4 2380.36   520.4 2380.44   523.9 2381.66   527.1 2383.69
   532.4 2385.19   550.5 2385.98   575.2 2390.15   589.5 2390.06   616.9 2392.65
   740.2  2401.7   813.3 2405.57   912.5    2414   922.2  2412.2941.0123 2412.32
#Mann= 6 ,-1,0
       0      .1       0     440     .08       0   505.7    .045       0
   523.9     .07       0  598.72     .05       0  868.72     .06       0
#XS Ineff= 2 , 0
           286.2 2385.13
Permanent Ineff=
       F       F
Bank Sta=505.7,523.9
XS Rating Curve= 0 ,0
Exp/Cntr(USF)=0,0
Exp/Cntr=0.3,0.1

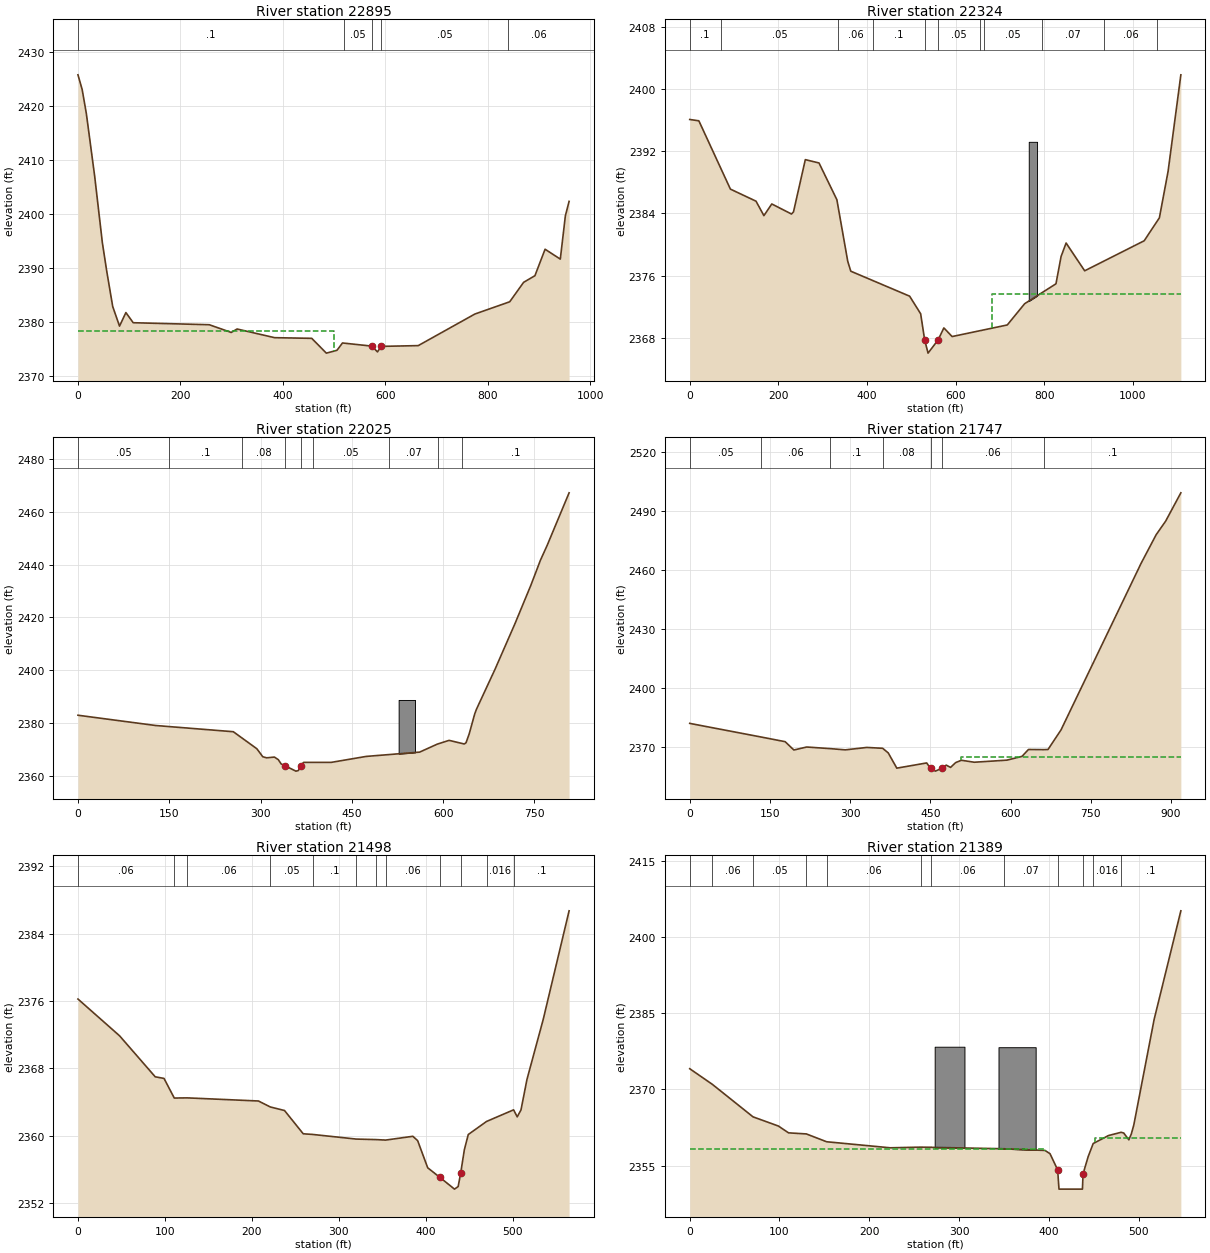
Type RM Length L Ch R = 1 ,22895   ,570.7,570.5,539.2
XS GIS Cut Line= 3
2261834.15800968448620.2478105332261348.48494407448987.784184511
2261066.26951405449193.429536617
#Sta/Elev= 30
       0 2425.75     8.2 2423.03    16.4 2418.54    32.6 2406.97    47.6 2394.65
    56.3 2389.28    67.8 2382.84    81.1 2379.21    93.5 2381.72   107.8 2379.84
   256.2 2379.47     299 2378.04   310.5 2378.68   383.7 2377.07   456.1 2376.95
   484.6 2374.21   505.3 2374.73   516.1 2376.09   573.2 2375.51   584.4 2374.44
  591.56 2375.46   663.9  2375.6   774.4 2381.45   842.4 2383.72   869.5 2387.32
   891.6 2388.55   911.4 2393.45   941.1 2391.62     951 2399.65958.2587 2402.31
#Mann= 5 ,-1,0
       0      .1       0     520     .05       0   573.2    .045       0
  591.56     .05       0  839.07     .06       0
#XS Ineff= 2 , 0
             500 2378.37
Permanent Ineff=
       F       F
Bank Sta=573.2,591.56
XS Rating Curve= 0 ,0
Exp/Cntr(USF)=0,0
Exp/Cntr=0.3,0.1

Type RM Length L Ch R = 1 ,22324   ,296.5,299.8,295.4
XS GIS Cut Line= 5
2261320.04462942448182.7045081792261190.96935522448447.418206103
2261011.57660126448688.0670223982260819.05754822448891.524657993
 2260628.7262117449027.163081722
#Sta/Elev= 30
       0 2396.07    20.6  2395.9    91.8 2387.12   149.6 2385.57   167.4 2383.71
   185.2 2385.21   229.7 2383.92   234.2  2384.2   260.9 2390.91   291.8 2390.48
   332.1 2385.76   356.6 2377.85   363.5 2376.57   496.3 2373.36   521.2  2371.1
  530.23 2367.75   537.9 2366.04   560.7 2367.75   573.6 2369.28   592.2 2368.17
   716.7 2369.66   755.9 2372.39   826.6 2374.95   838.2 2378.47   849.5 2380.19
   891.4 2376.62  1025.7 2380.48    1060 2383.43  1079.7 2389.421108.484 2401.81
#Mann= 11 ,-1,0
       0      .1       0      70     .05       0  334.51     .06       0
  414.51      .1       0  530.23    .045       0   560.7     .05       0
  654.66     .07       0  664.66     .05       0  794.66     .07       0
  934.77     .06       0 1054.77      .1       0
#XS Ineff= 2 , 0
                          681.73         2373.68
Permanent Ineff=
       F       F
#Block Obstruct= 1 ,-1
  765.17  783.92  2393.2
Bank Sta=530.23,560.7
XS Rating Curve= 0 ,0
Exp/Cntr(USF)=0,0
Exp/Cntr=0.3,0.1

Type RM Length L Ch R = 1 ,22025   ,288.9,278,269.1
XS GIS Cut Line= 4
2260991.50660165448209.4133938872260849.32610549448468.471077561
2260757.75222661448581.7335067022260551.71099913448884.168290899
#Sta/Elev= 30
       0 2383.05   127.5 2379.17   255.3 2376.82   293.9 2370.39   303.7 2367.36
   310.1 2366.95   322.8 2367.23   329.2 2366.26   333.8 2364.66   339.5 2364.04
   358.1 2361.92   362.2 2362.14  366.35 2364.04   370.8 2365.23   416.3 2365.23
   473.6 2367.48   561.5 2369.11   590.5 2372.13   609.9 2373.55   634.8 2372.18
   637.7 2372.63   642.9 2375.98     652 2383.55   654.9 2385.33   685.5 2400.49
   718.3 2417.75   744.2 2432.15   759.9  2441.6   770.8 2447.13   807.1 2467.13
#Mann= 9 ,-1,0
       0     .05       0     150      .1       0     270     .08       0
   339.5    .045       0  366.35     .08       0  385.51     .05       0
  511.16     .07       0  591.16     .06       0  631.16      .1       0
#Block Obstruct= 1 ,-1
  526.95  553.93 2388.83
Bank Sta=339.5,366.35
XS Rating Curve= 0 ,0
Exp/Cntr(USF)=0,0
Exp/Cntr=0.3,0.1

Type RM Length L Ch R = 1 ,21747   ,232.1,248.5,255.3
XS GIS Cut Line= 3
     2260589.093      447987.019     2260555.158      448447.424
     2260485.245       448898.64
#Sta/Elev= 30
       0 2381.84   133.6  2374.9   178.4 2372.54   194.7 2368.31   218.8 2369.83
   262.9    2369   290.9 2368.38   331.1 2369.61   360.7 2369.18   371.2 2366.82
   387.2 2359.08     443 2361.73   450.22358.991   459.4 2357.57   471.5 2359.02
   479.6 2360.62   487.7 2359.46   497.3 2361.92     508 2363.09     532 2362.09
     593 2363.15   621.3 2365.08   633.4 2368.57   661.8  2368.5   669.9 2368.57
   694.2 2378.51   843.9 2463.17   872.1 2477.73   889.9 2484.65   918.3 2499.03
#Mann= 7 ,-1,0
       0     .05       0   133.6     .06       0   262.9      .1       0
   360.7     .08       0   450.2    .045       0   471.5     .06       0
   661.8      .1       0
#XS Ineff= 2 , 0
                           508.1            2365
Permanent Ineff=
       F       F
Bank Sta=450.2,471.5
XS Rating Curve= 0 ,0
Exp/Cntr=0.3,0.1

Type RM Length L Ch R = 1 ,21498   ,112.1,109.5,109.4
XS GIS Cut Line= 6
2260556.48018052448051.2636465212260407.60778953448323.260881867
2260398.15669996 448330.381992952260360.04281782448365.991939607
2260306.86454546448416.1963322692260224.33630403448499.542040133
#Sta/Elev= 30
       0 2376.24    47.8 2371.88    88.8 2367.01    98.9 2366.82   110.7 2364.49
   125.6 2364.51   207.4 2364.14   221.1 2363.43   237.4 2363.01   258.9 2360.25
   269.8 2360.17   319.9 2359.62   342.3 2359.56   353.6  2359.5   384.9 2359.95
   390.4 2359.44     402 2356.21   415.8 2355.09   432.8 2353.68     437 2353.99
   439.9 2355.58   444.1 2358.35   448.6 2360.16   469.6 2361.71   500.7 2363.09
   504.9 2362.26   509.2 2363.08   516.1 2366.71   534.7  2373.8   564.5 2386.71
#Mann= 12 ,-1,0
       0     .06       0   110.7    .016       0   125.6     .06       0
   221.1     .05       0   269.8      .1       0   319.9     .05       0
   342.3      .1       0   353.6     .06       0   415.8    .045       0
   439.9     .06       0   469.6    .016       0   500.7      .1       0
Bank Sta=415.8,439.9
XS Rating Curve= 0 ,0
Exp/Cntr(USF)=0,0
Minor Loss Coefficient=0
Exp/Cntr=0.3,0.3

Type RM Length L Ch R = 1 ,21389   ,46.3,47.2,47.7
BEGIN DESCRIPTION:
Channel burned based on survey BRO062CU
END DESCRIPTION:
XS GIS Cut Line= 3
2260530.05199255448043.3263909612260187.71844094448385.659942565
2260142.50457564448429.581983149
#Sta/Elev= 30
       0 2374.09    25.3    2371    70.5 2364.62    98.8 2362.81   110.1 2361.47
   129.9 2361.26   152.5 2359.72   223.3 2358.53   257.2 2358.66   268.5 2358.63
   268.5 2358.62   350.5 2358.34   395.8 2358.01   401.4 2357.37   409.9 2354.19
   411.4  2350.4  437.52  2350.4   438.2 2353.37   438.2 2353.38   438.2 2353.39
   443.9 2356.79   449.5 2359.37   466.5 2360.94   480.6 2361.58   483.5 2361.44
   489.2 2360.11     492 2361.26   494.8 2363.07   517.4 2383.79 547.168 2405.15
#Mann= 12 ,-1,0
       0     .05       0    25.3     .06       0    70.5     .05       0
   129.9    .016       0   152.5     .06       0   257.2    .016       0
   268.5     .06       0   350.5     .07       0   409.9    .045       0
   438.2     .06       0   449.5    .016       0   480.6      .1       0
#XS Ineff= 2 , 0
             396  2358.3     452         2360.39
Permanent Ineff=
       F       F
#Block Obstruct= 2 ,-1
  272.89  306.08 2378.42  343.99   385.4 2378.32
Bank Sta=409.9,438.2
XS Rating Curve= 0 ,0
Exp/Cntr(USF)=0,0
Exp/Cntr=0.5,0.3

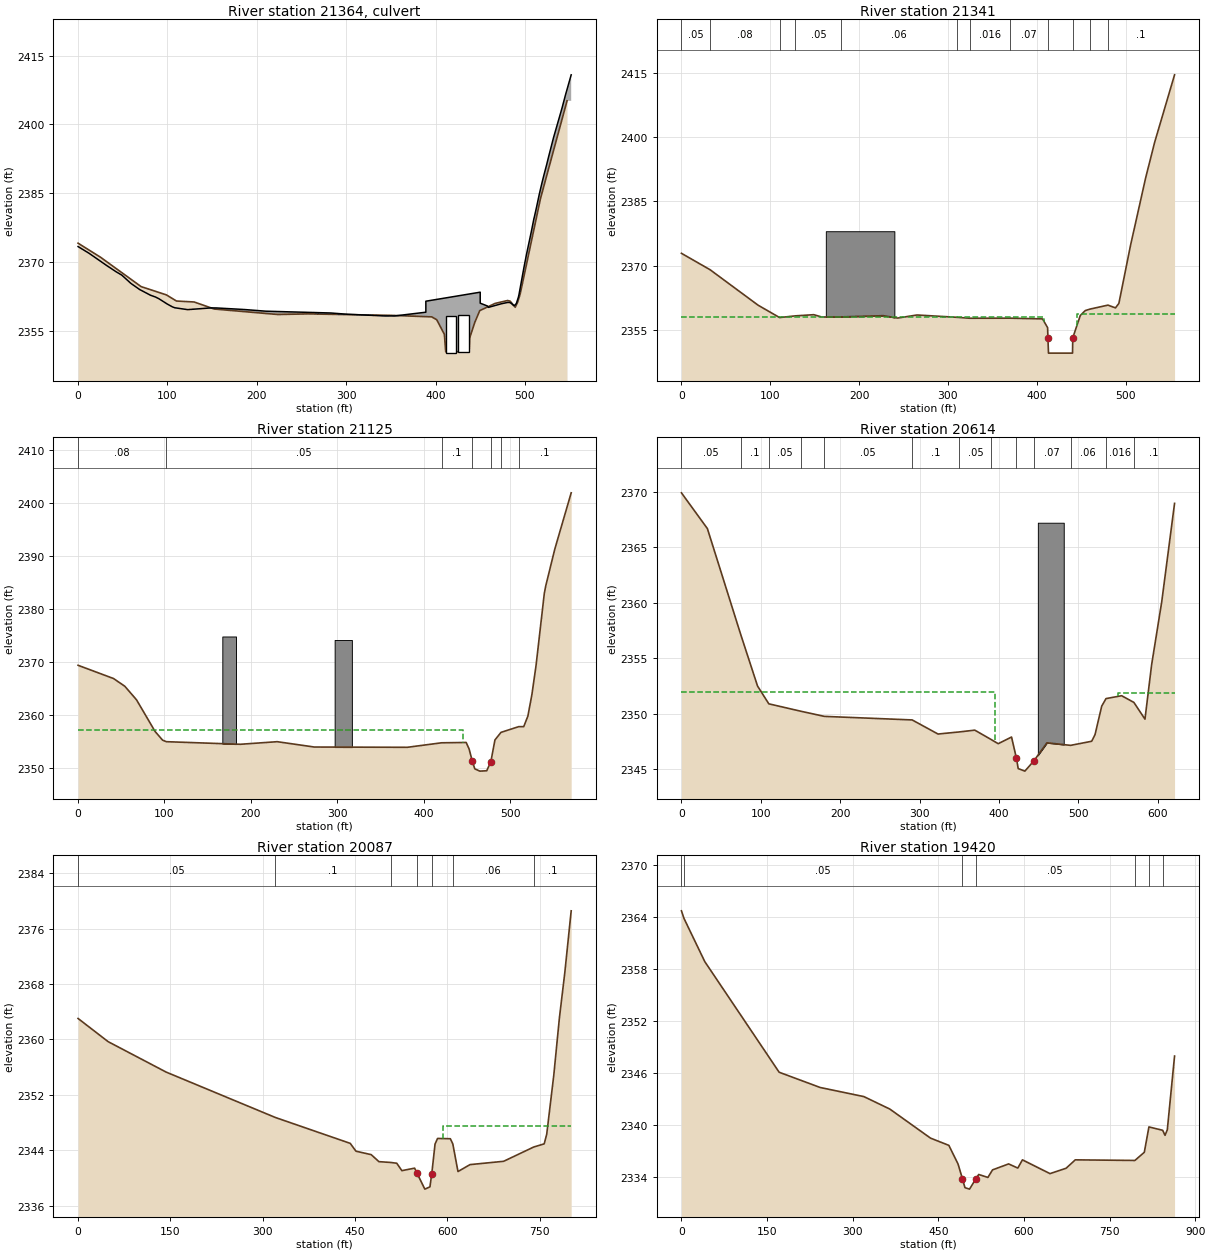
Type RM Length L Ch R = 2 ,21364   ,,,
BEGIN DESCRIPTION:
Luster Shrader Road
Survey ID:54075BRO060
END DESCRIPTION:
Bridge Culvert--1,0,-1,-1, 0
Deck Dist Width WeirC Skew NumUp NumDn MinLoCord MaxHiCord MaxSubmerge Is_Ogee
15,23,2.6,0, 52, 52, , , 0.98, 0, 0,0,,
       0    12.2    31.6    42.6      49    59.1    68.8    81.2    86.7    90.7
    99.9   105.6   108.2   122.6   148.9   154.7   185.8   210.3   282.8   300.8
   343.3   354.6  389.15  389.15     450     450  457.99   459.3   473.4   480.7
   483.1   484.8   487.6   488.3   490.4   492.5   493.3   498.9   501.7   507.4
   510.2   510.3   513.1   516.1   518.7   521.1   524.4   526.5     532   541.4
   545.7   551.8
 2373.35  2371.9 2369.27 2367.85 2367.11 2365.32 2363.99 2362.72 2362.34 2361.94
  2360.8 2360.19    2360 2359.59 2359.97 2359.96 2359.62 2359.25 2358.86 2358.59
 2358.21 2358.22 2359.03 2361.43  2363.4    2361 2360.39 2360.09 2360.86 2361.16
 2361.14 2360.95 2360.48 2360.47 2360.92 2362.17 2362.79 2368.77 2371.58 2376.82
 2379.56 2379.58 2382.02 2384.78 2386.94 2388.83 2391.27 2392.94 2397.11 2403.49
 2406.65 2410.83
                                                                                
                                                                                
                                                                                
                                                                                
                                                                                
                
       0    12.2    31.6    42.6      49    59.1    68.8    81.2    86.7    90.7
    99.9   105.6   108.2   122.6   148.9   154.7   185.8   210.3   282.8   300.8
   343.3   354.6  389.15  389.15     450     450  457.99   459.3   473.4   480.7
   483.1   484.8   487.6   488.3   490.4   492.5   493.3   498.9   501.7   507.4
   510.2   510.3   513.1   516.1   518.7   521.1   524.4   526.5     532   541.4
   545.7   551.8
 2373.35  2371.9 2369.27 2367.85 2367.11 2365.32 2363.99 2362.72 2362.34 2361.94
  2360.8 2360.19    2360 2359.59 2359.97 2359.96 2359.62 2359.25 2358.86 2358.59
 2358.21 2358.22 2359.03 2361.43  2363.4    2361 2360.39 2360.09 2360.86 2361.16
 2361.14 2360.95 2360.48 2360.47 2360.92 2362.17 2362.79 2368.77 2371.58 2376.82
 2379.56 2379.58 2382.02 2384.78 2386.94 2388.83 2391.27 2392.94 2397.11 2403.49
 2406.65 2410.83
                                                                                
                                                                                
                                                                                
                                                                                
                                                                                
                
BR Coef=-1 ,-1 , 0 ,, 0 ,,,0.8,0,1.2,0,
WSPro=,,,, 1 ,,,, 0 ,,,, 0 ,,,,-1 ,-1 ,-1 , 0 , 0 , 0 , 0 , 0
Culvert=2,8,12,24,0.012,0.1,1,8,1,2350.1,417.4,2349.58,419.25,Culvert #1  , 0 ,14
   417.4  419.25
BC Culvert Barrel=1,Barrel1,0
Culvert Bottom n=0.045
Culvert=2,8,12,24,0.012,0.1,1,8,1,2350.38,431.52,2349.67,434.27,Culvert #2  , 0 ,14
  431.52  434.27
BC Culvert Barrel=1,Barrel2,0
Culvert Bottom n=0.045
BC Design=,, 0 ,, 0 ,,,,,,
BC Use User HTab Curves=0
BC User HTab FreeFlow(D)= 0

Type RM Length L Ch R = 1 ,21341   ,215.8,216.2,218.6
BEGIN DESCRIPTION:
Channel burned based on survey BRO058CD
END DESCRIPTION:
XS GIS Cut Line= 3
2260511.96644642448022.6571953922260156.71464759448346.905200874
 2260101.1661845 448395.99454035
#Sta/Elev= 30
       0 2372.85    32.2 2369.03    86.4 2360.74   110.5 2357.87   128.3 2358.27
   148.9 2358.54     158    2358     180 2358.03   227.2 2358.31   243.4 2357.75
   265.1 2358.47   310.3 2357.93   324.7 2357.71   369.7 2357.73   406.5 2357.56
   412.2 2355.52  412.55 2353.13   413.2 2349.58  440.27 2349.58   440.5 2353.11
     449 2358.36   454.6  2359.5     460 2359.85   480.1 2360.77   488.6 2360.13
   492.4 2361.16   505.6 2374.75   522.6 2390.46   532.7 2398.73555.1097 2414.46
#Mann= 12 ,-1,0
       0     .05       0    32.2     .08       0   110.5    .016       0
   128.3     .05       0     180     .06       0   310.3     .05       0
   324.7    .016       0   369.7     .07       0  412.55    .045       0
   440.5     .07       0     460    .016       0   480.1      .1       0
#XS Ineff= 2 , 0
           408.2    2358   445.2          2358.8
Permanent Ineff=
       F       F
#Block Obstruct= 1 ,-1
  162.53   239.7    2378
Bank Sta=412.55,440.5
XS Rating Curve= 0 ,0
Exp/Cntr(USF)=0,0
Exp/Cntr=0.5,0.3

Type RM Length L Ch R = 1 ,21125   ,505.4,510.9,504.2
XS GIS Cut Line= 4
2260461.68452819447925.4670155542260270.49955914448009.707059877
2260143.99558315448090.534032221  2259966.004336448205.152290977
#Sta/Elev= 30
       0 2369.34      41 2366.84    54.1 2365.38    67.7 2362.81    89.1 2356.85
    97.8  2355.2   102.2 2354.91   187.8 2354.42   230.5 2354.91   273.4  2353.9
   381.1 2353.85   420.7  2354.7   449.2 2354.76   452.6 2353.53   456.3 2351.22
   459.2 2349.78     465 2349.35     473 2349.42   477.8 2351.16   482.5 2355.24
   489.5 2356.67     510 2357.75   515.8 2357.75   520.6 2359.73   525.3 2363.83
   530.1 2369.34   539.6 2382.88   541.2 2384.27   551.8  2391.3570.7452 2401.91
#Mann= 7 ,-1,0
       0     .08       0   102.2     .05       0   420.7      .1       0
   456.3    .045       0   477.8     .06       0   489.5    .016       0
     510      .1       0
#XS Ineff= 2 , 0
          445.52 2357.15
Permanent Ineff=
       F       F
#Block Obstruct= 2 ,-1
  166.95  182.79 2374.78  296.95  316.91 2374.12
Bank Sta=456.3,477.8
XS Rating Curve= 0 ,0
Exp/Cntr(USF)=0,0
Exp/Cntr=0.3,0.1

Type RM Length L Ch R = 1 ,20614   ,521.8,527,521.7
Node Name=F
XS GIS Cut Line= 3
2260355.26164773447537.3281372062259869.58858211447697.031442566
2259764.57818955447729.847190242
#Sta/Elev= 30
       0 2369.89    32.7 2366.67    74.8 2357.11    95.9 2352.49   110.1 2350.89
   150.6 2350.22   180.1 2349.76   290.7 2349.44   323.3 2348.17   350.1 2348.36
   369.6 2348.52   390.6 2347.66   399.1  2347.3   415.9  2347.9   422.1 2345.97
   424.3 2345.06   432.7 2344.83   444.2 2345.77   460.5 2347.38   490.3 2347.15
   516.9 2347.52   521.1 2348.12   529.5 2350.68   534.9 2351.36   554.6 2351.62
     570 2351.02     584 2349.51   592.4 2354.42   605.1 2360.07621.2752 2368.94
#Mann= 13 ,-1,0
       0     .05       0    74.8      .1       0   110.1     .05       0
   150.6      .1       0   180.1     .05       0   290.7      .1       0
   350.1     .05       0   390.6     .06       0   422.1    .045       0
   444.2     .07       0   490.3     .06       0   534.9    .016       0
     570      .1       0
#XS Ineff= 2 , 0
             395    2352  549.75         2351.87
Permanent Ineff=
       F       F
#Block Obstruct= 1 ,-1
  449.03  481.66  2367.2
Bank Sta=422.1,444.2
XS Rating Curve= 0 ,0
Exp/Cntr(USF)=0,0
Exp/Cntr=0.3,0.1

Type RM Length L Ch R = 1 ,20087   ,581.4,667.8,571
XS GIS Cut Line= 4
2260279.79844398447064.547365538 2259872.8283518447158.698150605
  2259672.980264447213.2073291282259501.51798272447255.071404941
#Sta/Elev= 30
       0 2363.03    48.9 2359.68   143.3 2355.28   320.3 2348.74   442.3 2344.99
   451.6 2343.86   476.4 2343.36   488.9 2342.35   508.2 2342.23   517.9 2342.12
   526.2 2341.05   546.9 2341.41   551.1 2340.64   563.5 2338.38   571.8 2338.71
  574.78 2340.59   580.1 2344.89   584.2  2345.7     605 2345.66     609 2344.91
   617.4 2340.92   636.9 2341.92   691.6  2342.4   740.4 2344.46   757.5 2344.92
   761.6 2346.31   773.1 2354.85   782.2  2363.1     791 2369.66801.3664 2378.58
#Mann= 7 ,-1,0
       0     .05       0   320.3      .1       0   508.2     .08       0
   551.1    .045       0  574.78    .016       0     609     .06       0
   740.4      .1       0
#XS Ineff= 2 , 0
                           593.8         2347.46
Permanent Ineff=
       F       F
Bank Sta=551.1,574.78
XS Rating Curve= 0 ,0
Exp/Cntr(USF)=0,0
Exp/Cntr=0.3,0.1

Type RM Length L Ch R = 1 ,19420   ,476.4,548.3,442.4
XS GIS Cut Line= 6
2260376.62178061446550.3871079432260175.86889376446581.296021562
2259995.75097257446602.2721179012259924.47514944446609.163452495
2259631.59428279446644.4431856282259519.55394023446657.866099474
#Sta/Elev= 30
       0 2364.68     4.5  2363.8    40.9 2358.82   171.2 2346.05   243.1 2344.29
   319.6 2343.24   365.1  2341.8   436.3 2338.45   468.5 2337.61   484.6 2335.46
   492.3 2333.75   496.7 2332.73   504.7 2332.56  515.54 2333.71   520.8 2334.25
   536.9 2333.91     545 2334.78   573.2 2335.47   589.3 2334.99   597.4 2335.94
   645.7 2334.35   673.9 2334.97     690 2335.94   794.4 2335.87   810.9 2336.81
     819 2339.74   843.1 2339.35   847.2 2338.77   851.2 2339.41863.9014 2347.92
#Mann= 7 ,-1,0
       0      .1       0     4.5     .05       0   492.3    .045       0
  515.54     .05       0   794.4      .1       0     819    .016       0
   843.1      .1       0
Bank Sta=492.3,515.54
XS Rating Curve= 0 ,0
Exp/Cntr(USF)=0,0
Exp/Cntr=0.3,0.1

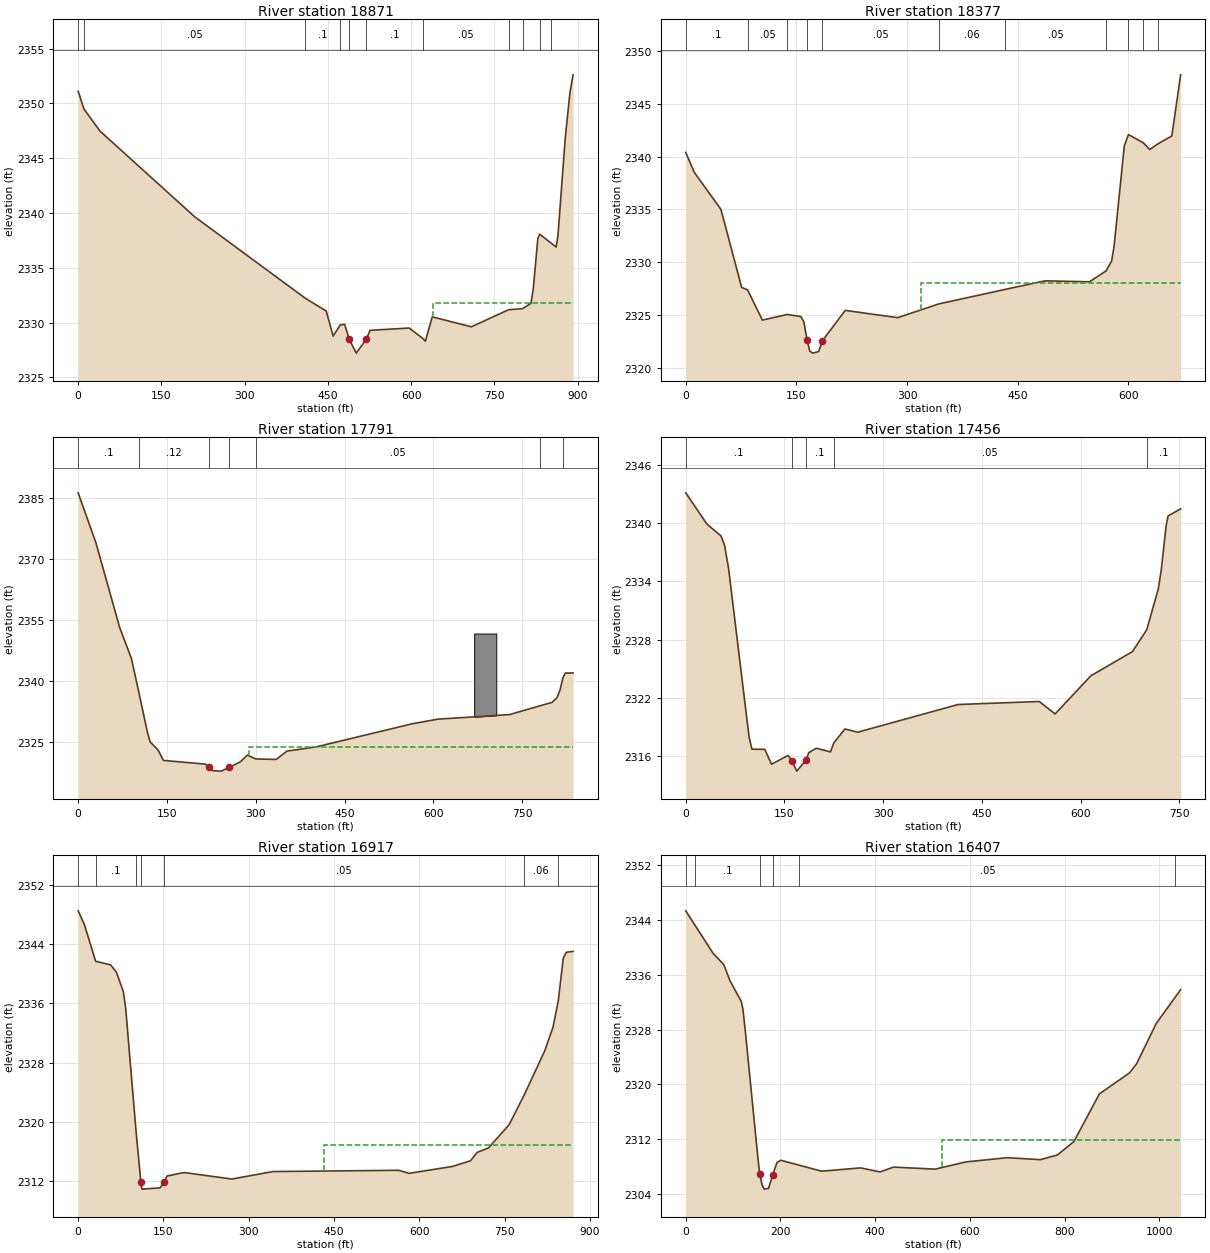
Type RM Length L Ch R = 1 ,18871   ,465.7,494.4,490.1
XS GIS Cut Line= 5
2260242.20348932446036.0662374642259893.78740016446134.253063045
2259734.30339804446179.9337843642259534.75042877446234.410553325
2259382.58368576446272.653789021
#Sta/Elev= 30
       0 2351.11    10.4  2349.5    39.5 2347.47   209.9 2339.66   409.4 2332.22
   446.9 2331.06   459.4 2328.78   472.4 2329.81   480.2 2329.84   488.4 2328.47
     501 2327.22  519.14 2328.49   525.9  2329.3   596.4 2329.51   620.4 2328.58
   625.5 2328.31   637.9 2330.53   708.4 2329.62   775.4 2331.18   800.6 2331.28
   815.8 2331.76   819.9 2333.09   828.1 2337.65   831.4 2338.08   851.2 2337.29
   861.1  2336.9   864.4 2337.95   877.6 2346.89   885.9 2350.96891.6381 2352.61
#Mann= 11 ,-1,0
       0      .1       0    10.4     .05       0   409.4      .1       0
   472.4     .05       0   488.4    .045       0  519.14      .1       0
   620.4     .05       0   775.4     .06       0   800.6      .1       0
   831.4    .016       0   851.2      .1       0
#XS Ineff= 2 , 0
                             640         2331.82
Permanent Ineff=
       F       F
Bank Sta=488.4,519.14
XS Rating Curve= 0 ,0
Exp/Cntr(USF)=0,0
Exp/Cntr=0.3,0.1

Type RM Length L Ch R = 1 ,18377   ,560.9,586.2,511.9
XS GIS Cut Line= 4
2259823.64653537445704.0217003422259737.61355579445711.947396922
2259553.18823373445725.534301725 2259181.0466618 445870.94289931
#Sta/Elev= 30
       0 2340.39    11.6  2338.5    47.7 2334.99    75.8 2327.59    83.8 2327.37
   103.9  2324.5   137.5 2325.03     156 2324.84     160 2324.35   164.6 2322.58
   168.1 2321.56   172.1 2321.37   180.1 2321.51  185.34 2322.55   216.2 2325.42
   287.3 2324.73   342.9 2326.03   432.4  2327.4   487.1 2328.22   547.3 2328.13
   569.8 2329.16   577.3  2330.1   580.6 2331.46   594.5 2341.01   600.1 2342.08
   620.3  2341.3   628.9 2340.66   640.3 2341.21   658.9 2341.95   670.9 2347.74
#Mann= 11 ,-1,0
       0      .1       0    83.8     .05       0   137.5      .1       0
   164.6    .045       0  185.34     .05       0   342.9     .06       0
   432.4     .05       0   569.8     .07       0   600.1    .016       0
   620.3     .06       0   640.3     .08       0
#XS Ineff= 2 , 0
                          319.04         2327.99
Permanent Ineff=
       F       F
Bank Sta=164.6,185.34
XS Rating Curve= 0 ,0
Exp/Cntr(USF)=0,0
Exp/Cntr=0.3,0.1

Type RM Length L Ch R = 1 ,17791   ,326.1,334.5,340.3
XS GIS Cut Line= 5
2259774.55803399 445092.54777255 2259674.7655615445148.303029922
2259596.66470115445187.3872396672259472.52291455445255.875159791
2259032.30978845445477.393154314
#Sta/Elev= 30
       0 2386.15    30.2 2373.82    69.8 2353.29    89.8 2345.63   102.2 2337.48
   117.2 2327.35   121.7 2325.09   135.1 2323.12     144 2320.57   215.1 2319.67
   220.5 2318.87   226.9 2318.06   241.6 2317.95     255 2318.85     274 2320.23
   285.8 2321.88   300.2 2320.93   334.7 2320.82   352.8 2322.86     402 2323.88
   565.1 2329.58     608 2330.69     729 2331.81   779.6 2333.93   800.6 2334.79
   809.1 2335.96     814 2337.76     819 2340.78     823 2341.98   836.2    2342
#Mann= 7 ,-1,0
       0      .1       0   102.2     .12       0   220.5    .045       0
     255      .1       0   300.2     .05       0   779.6     .08       0
     819    .016       0
#XS Ineff= 2 , 0
                          289.01         2323.87
Permanent Ineff=
       F       F
#Block Obstruct= 1 ,-1
  669.07  706.43 2351.67
Bank Sta=220.5,255
XS Rating Curve= 0 ,0
Exp/Cntr(USF)=0,0
Exp/Cntr=0.3,0.1

Type RM Length L Ch R = 1 ,17456   ,529.3,538.7,533.8
Node Name=E
XS GIS Cut Line= 3
2259554.55740442444863.9385598222259351.09976882444938.320921222
2258865.42670321445163.655721935
#Sta/Elev= 30
       0 2343.12    32.3 2339.89    53.6 2338.68      59 2337.71    65.2 2335.28
    96.2 2317.99   100.5 2316.72   120.1  2316.7   130.3 2315.17   155.6 2316.08
   161.9 2315.46   168.6 2314.46   183.2 2315.63   186.8 2316.36   198.4 2316.82
   219.9 2316.44     225 2317.37   241.9  2318.8   261.4 2318.47   413.8 2321.32
   537.2 2321.63   561.3 2320.35   615.6 2324.28   678.8 2326.77   700.5 2329.02
     718 2333.22   722.5 2335.15     730 2339.77     733 2340.75 752.029 2341.47
#Mann= 5 ,-1,0
       0      .1       0   161.9    .045       0   183.2      .1       0
     225     .05       0   700.5      .1       0
Bank Sta=161.9,183.2
XS Rating Curve= 0 ,0
Exp/Cntr(USF)=0,0
Exp/Cntr=0.3,0.1

Type RM Length L Ch R = 1 ,16917   ,513.8,510.2,463.7
XS GIS Cut Line= 3
2259418.91898069444389.2040767682259236.04425198444415.003850921
2258628.40585807444733.222666828
#Sta/Elev= 30
       0 2348.47    10.9 2346.64    30.7 2341.67    57.1 2341.18    67.4 2340.17
    79.5 2337.57    83.6 2335.32   101.5 2319.02  110.33 2311.85   112.2 2310.93
     144  2311.1   151.1 2311.83   156.3  2312.7   186.2 2313.17   270.3 2312.29
   342.6  2313.3   563.8 2313.47   581.9 2313.06   658.6 2313.99   690.3 2314.76
   701.8 2315.88   721.9  2316.5     758 2319.61   784.8 2323.66   820.4 2329.53
   835.2 2332.75   844.6 2336.35   853.3 2342.08   858.9 2342.88   870.6    2343
#Mann= 7 ,-1,0
       0     .12       0    30.7      .1       0   101.5     .12       0
  110.33    .045       0   151.1     .05       0   784.8     .06       0
   844.6      .1       0
#XS Ineff= 2 , 0
                          432.01         2316.85
Permanent Ineff=
       F       F
Bank Sta=110.33,151.1
XS Rating Curve= 0 ,0
Exp/Cntr(USF)=0,0
Exp/Cntr=0.3,0.1

Type RM Length L Ch R = 1 ,16407   ,312.7,312.8,221
XS GIS Cut Line= 3
2259407.98039813443826.9609332422259136.70355067443964.787073484
2258495.70261272444336.698880485
#Sta/Elev= 30
       0 2345.33    57.9 2339.12    80.5 2337.47    93.7 2335.09   117.5 2332.09
   120.9 2330.91   126.5 2327.32   152.3 2309.33   156.2    2307   161.3 2305.31
   165.8 2304.72   174.8 2304.83   183.7 2306.78   192.7 2308.61   200.8 2308.93
   286.9 2307.34   369.3 2307.82   410.3 2307.23     439 2307.93   526.9 2307.64
   591.8 2308.69   679.2 2309.31   748.8 2309.02   784.9  2309.7     820 2311.67
   873.7 2318.62   937.1 2321.67   952.3 2323.02   993.9 2328.911045.362 2333.83
#Mann= 6 ,-1,0
       0     .12       0      20      .1       0   156.2    .045       0
   183.7      .1       0     240     .05       0 1034.28     .06       0
#XS Ineff= 2 , 0
                          541.86         2311.85
Permanent Ineff=
       F       F
Bank Sta=156.2,183.7
XS Rating Curve= 0 ,0
Exp/Cntr(USF)=0,0
Exp/Cntr=0.3,0.1