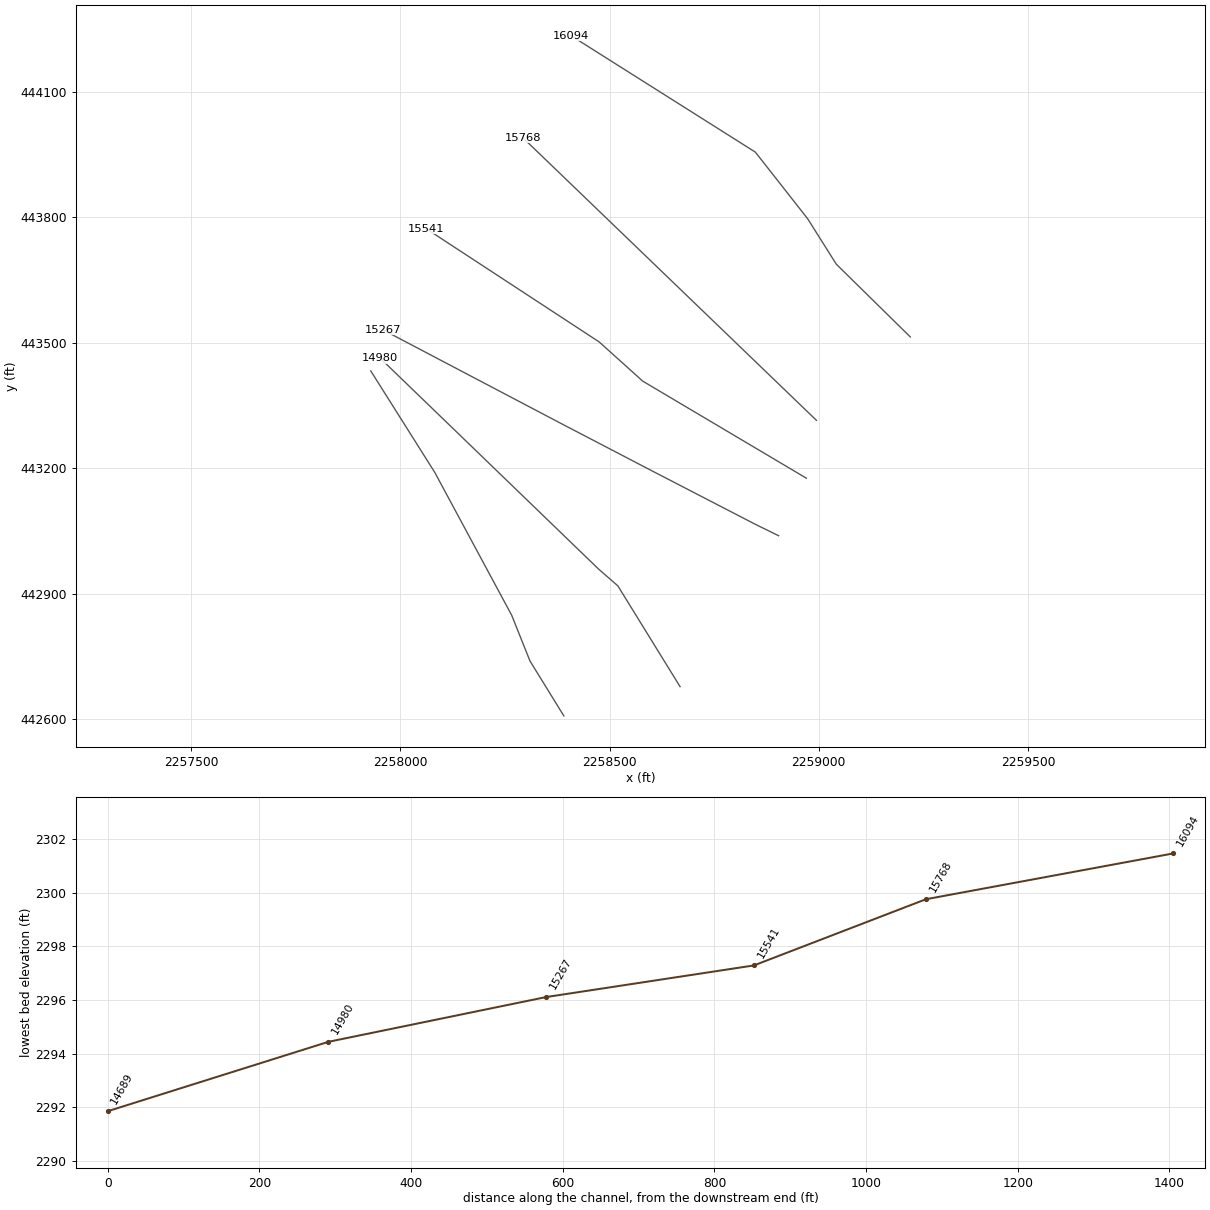
HEC-RAS study BRWNSCK.prj: BRWNSCK

--- BRWNSCK.g01 (geometry) --- (continued)

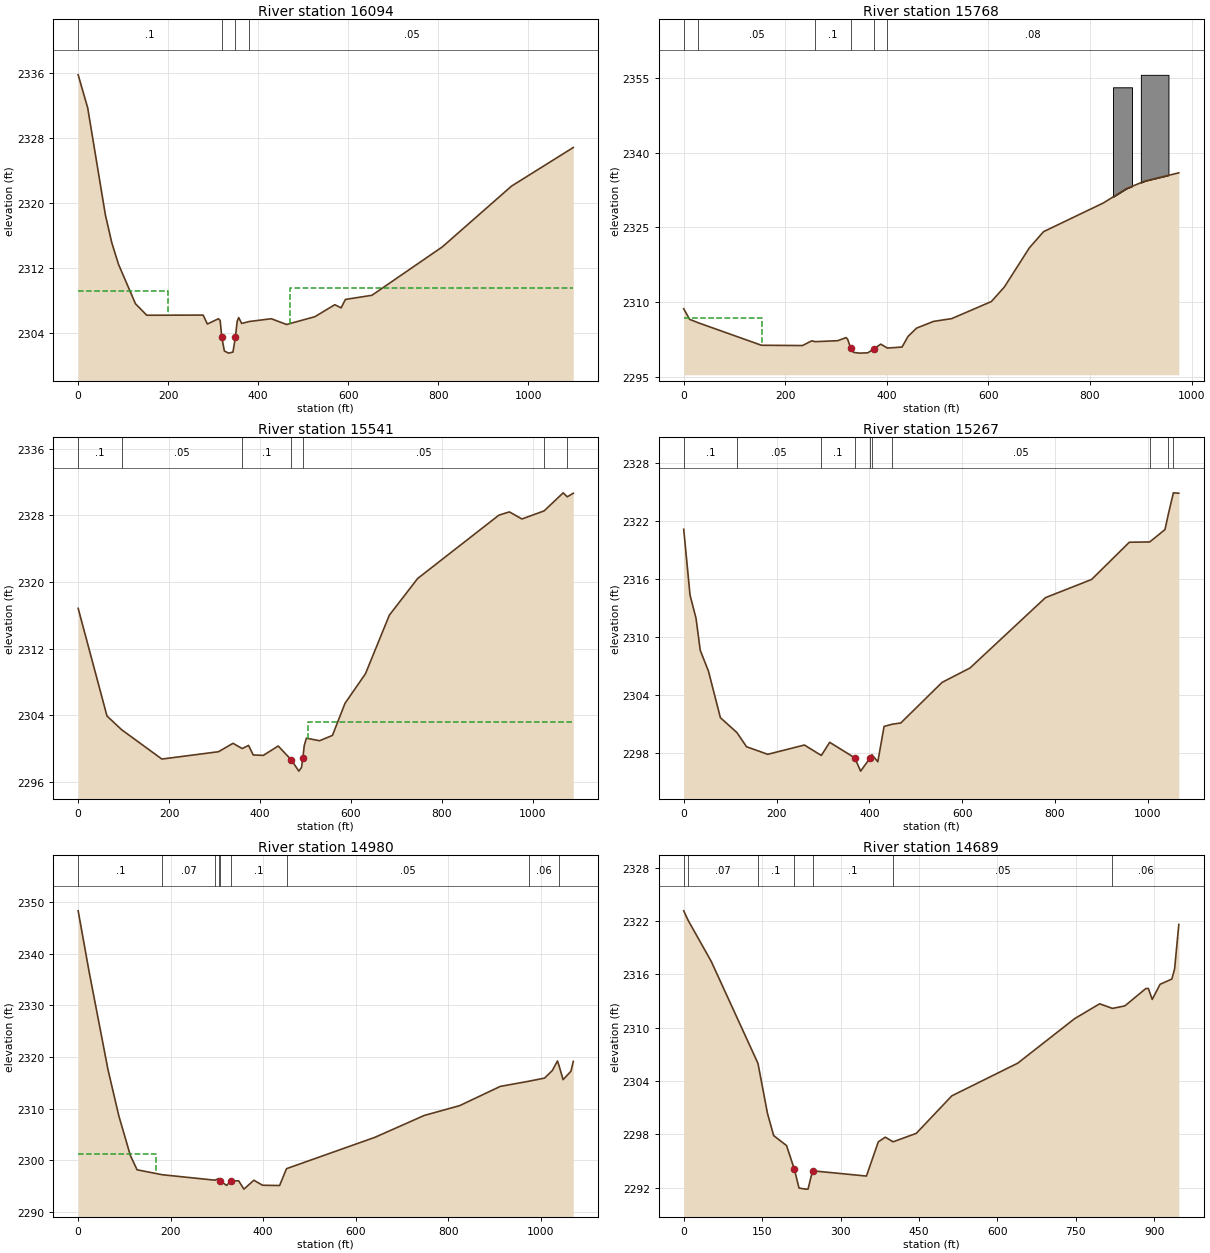
Type RM Length L Ch R = 1 ,16094   ,312.7,326.4,340.7
XS GIS Cut Line= 5
2259218.94833202443514.3323710042259041.92930039443688.376292852
2258973.50177557443796.9677996462258848.54716501443956.136172618
2258408.23091828444234.308936598
#Sta/Elev= 30
       0 2335.78    21.2  2331.7    60.5  2318.5    74.7 2315.08    89.6 2312.42
   127.3 2307.56   152.4 2306.14   277.6 2306.16     287 2305.06   311.6 2305.71
   315.4  2305.5   319.1  2303.4   324.8 2301.73   334.2 2301.47   343.8  2301.6
  349.14  2303.4   353.2 2305.38   356.6 2305.85   363.2 2305.13   380.5 2305.37
     429 2305.71     463    2305   525.8 2305.96   570.1 2307.44   584.1 2307.05
   593.6 2308.09   652.5  2308.6     809 2314.57   962.6 2322.06  1099.8 2326.82
#Mann= 4 ,-1,0
       0      .1       0   319.1    .045       0  349.14     .08       0
   380.5     .05       0
#XS Ineff= 2 , 0
          199.34 2309.17  470.93         2309.48
Permanent Ineff=
       F       F
Bank Sta=319.1,349.14
XS Rating Curve= 0 ,0
Exp/Cntr(USF)=0,0
Exp/Cntr=0.3,0.1

Type RM Length L Ch R = 1 ,15768   ,206.1,226.8,224
XS GIS Cut Line= 3
 2258994.5019774443315.0352694882258642.27961901443654.131328812
2258292.24497713443991.039671625
#Sta/Elev= 30
       0 2308.66    11.6 2306.54    28.6 2305.85     153 2301.34   233.8 2301.28
   252.1 2302.23   258.6 2302.06   303.1 2302.25   319.7 2302.87   322.8 2302.53
   328.5 2300.83   334.1 2299.92   345.5 2299.76   362.4 2299.82   375.2 2300.66
   387.9 2301.56     401 2300.78   429.9 2300.98   441.6 2303.11   458.5 2304.78
   491.8 2306.12   527.9 2306.69   605.7 2310.11   631.2 2313.01   680.6 2320.89
   708.4 2324.12   826.4 2329.89   871.6 2332.75   908.6 2334.29974.7548 2335.92
#Mann= 6 ,-1,0
       0      .1       0    28.6     .05       0   258.6      .1       0
   328.5    .045       0   375.2      .1       0     401     .08       0
#XS Ineff= 2 , 0
          154.49 2306.73
Permanent Ineff=
       F       F
#Block Obstruct= 2 ,-1
  845.11  882.66 2353.08  900.03  954.38 2355.58
Bank Sta=328.5,375.2
XS Rating Curve= 0 ,0
Exp/Cntr(USF)=0,0
Exp/Cntr=0.3,0.1

Type RM Length L Ch R = 1 ,15541   ,175.7,274,233.3
XS GIS Cut Line= 4
2258970.52666579443176.6574115212258579.29973035443408.715973985
2258475.17088822443502.4319319032258061.63062947443773.166921445
#Sta/Elev= 30
       0 2316.84    63.4 2303.91    95.7 2302.26   184.1 2298.74   308.6 2299.62
   340.7 2300.63   360.8    2300   374.8 2300.38   385.2 2299.23   407.3 2299.18
   440.1 2300.31   468.7 2298.65   485.5 2297.29   491.4 2297.74   494.2 2298.86
   497.4 2300.36   502.1 2301.25   531.1 2300.94   559.4 2301.58   587.1 2305.44
     632 2308.98   684.6 2316.02   746.8 2320.42   925.6 2328.03   948.7 2328.42
   976.2 2327.57    1025 2328.54  1067.1 2330.71  1075.9 2330.23  1089.2 2330.66
#Mann= 7 ,-1,0
       0      .1       0    95.7     .05       0   360.8      .1       0
   468.7    .045       0   494.2     .05       0    1025     .06       0
  1075.9    .016       0
#XS Ineff= 2 , 0
                          506.37         2303.14
Permanent Ineff=
       F       F
Bank Sta=468.7,494.2
XS Rating Curve= 0 ,0
Exp/Cntr(USF)=0,0
Exp/Cntr=0.3,0.1

Type RM Length L Ch R = 1 ,15267   ,303.5,287,246
XS GIS Cut Line= 5
2258904.10076828443039.2014959772258848.11730791443066.635642714
2258605.70699326 443192.027067862258386.31678713443306.284403441
2257957.84808967443531.532262478
#Sta/Elev= 30
       0 2321.12    13.6 2314.32    26.6  2311.9    35.6 2308.61    53.4 2306.44
      79 2301.64   114.6  2300.1   135.4 2298.63   181.1 2297.85   260.1 2298.81
   296.5 2297.73   314.5 2299.09   368.6 2297.48   381.1 2296.11  402.15  2297.5
   405.5 2297.81   418.2 2297.08   431.7 2300.73   449.1 2300.96   467.7 2301.09
   556.7 2305.29   616.7 2306.77   779.4 2314.05   878.8 2315.93   960.1 2319.78
    1004 2319.81  1036.9 2321.09  1044.4 2322.74    1055 2324.89  1066.7 2324.85
#Mann= 10 ,-1,0
       0      .1       0   114.6     .05       0   296.5      .1       0
   368.6    .045       0  402.15      .1       0   405.5     .07       0
   449.1     .05       0    1004     .06       0  1044.4     .07       0
    1055    .016       0
Bank Sta=368.6,402.15
XS Rating Curve= 0 ,0
Exp/Cntr(USF)=0,0
Exp/Cntr=0.3,0.1

Type RM Length L Ch R = 1 ,14980   ,270.5,291.1,216.9
XS GIS Cut Line= 4
2258668.55302361442678.3265241782258519.79753485442919.310415968
2258473.68333334442959.4743979332257951.55156779443463.755504826
#Sta/Elev= 30
       0 2348.27    23.6 2336.52    64.5 2317.54      88 2308.58   112.8 2300.96
   127.3 2298.18     182 2297.22   295.6 2296.17   303.9 2296.49   306.9 2296.04
   321.1 2295.16   329.6 2296.01   346.8 2296.05   358.3 2294.44   379.8 2296.16
   398.6 2295.19   435.4 2295.14   450.4  2298.4   641.2 2304.45   748.3  2308.7
   824.7 2310.59   912.4 2314.31   974.8 2315.32  1008.2 2315.92  1024.9 2317.38
    1036 2319.23  1039.7 2318.25  1048.2 2315.61  1065.2 2317.25  1070.2 2319.15
#Mann= 9 ,-1,0
       0      .1       0     182     .07       0   295.6      .1       0
   303.9     .08       0   306.9    .045       0   329.6      .1       0
   450.4     .05       0   974.8     .06       0  1039.7      .1       0
#XS Ineff= 2 , 0
          167.44 2301.27
Permanent Ineff=
       F       F
Bank Sta=306.9,329.6
XS Rating Curve= 0 ,0
Exp/Cntr(USF)=0,0
Exp/Cntr=0.3,0.1

Type RM Length L Ch R = 1 ,14689   ,187.2,207.9,172.3
XS GIS Cut Line= 5
2258390.69222016442608.4028361862258309.74670922442739.665826892
2258265.99237899442849.051652481  2258082.224192443190.335428317
2257929.08403617443433.171961123
#Sta/Elev= 30
       0 2323.14     8.2  2322.1    52.6 2317.46     142 2305.99   160.2 2300.36
     172 2297.87   196.6 2296.75   211.6 2294.09   220.5 2291.97   233.4 2291.85
   237.7 2291.85   246.3 2293.91   349.4 2293.32   372.1 2297.17   385.5 2297.69
   400.4 2297.17   444.7 2298.12   512.7 2302.34   638.7 2306.01   747.3 2311.01
   795.4 2312.69   819.8 2312.17   843.5 2312.45   883.6  2314.4   888.4 2314.42
   895.9 2313.18   910.9 2314.88   933.4 2315.47   938.7 2316.61946.7332 2321.61
#Mann= 7 ,-1,0
       0      .1       0     8.2     .07       0     142      .1       0
   211.6    .045       0   246.3      .1       0   400.4     .05       0
   819.8     .06       0
Bank Sta=211.6,246.3
XS Rating Curve= 0 ,0
Exp/Cntr(USF)=0,0
Exp/Cntr=0.3,0.1