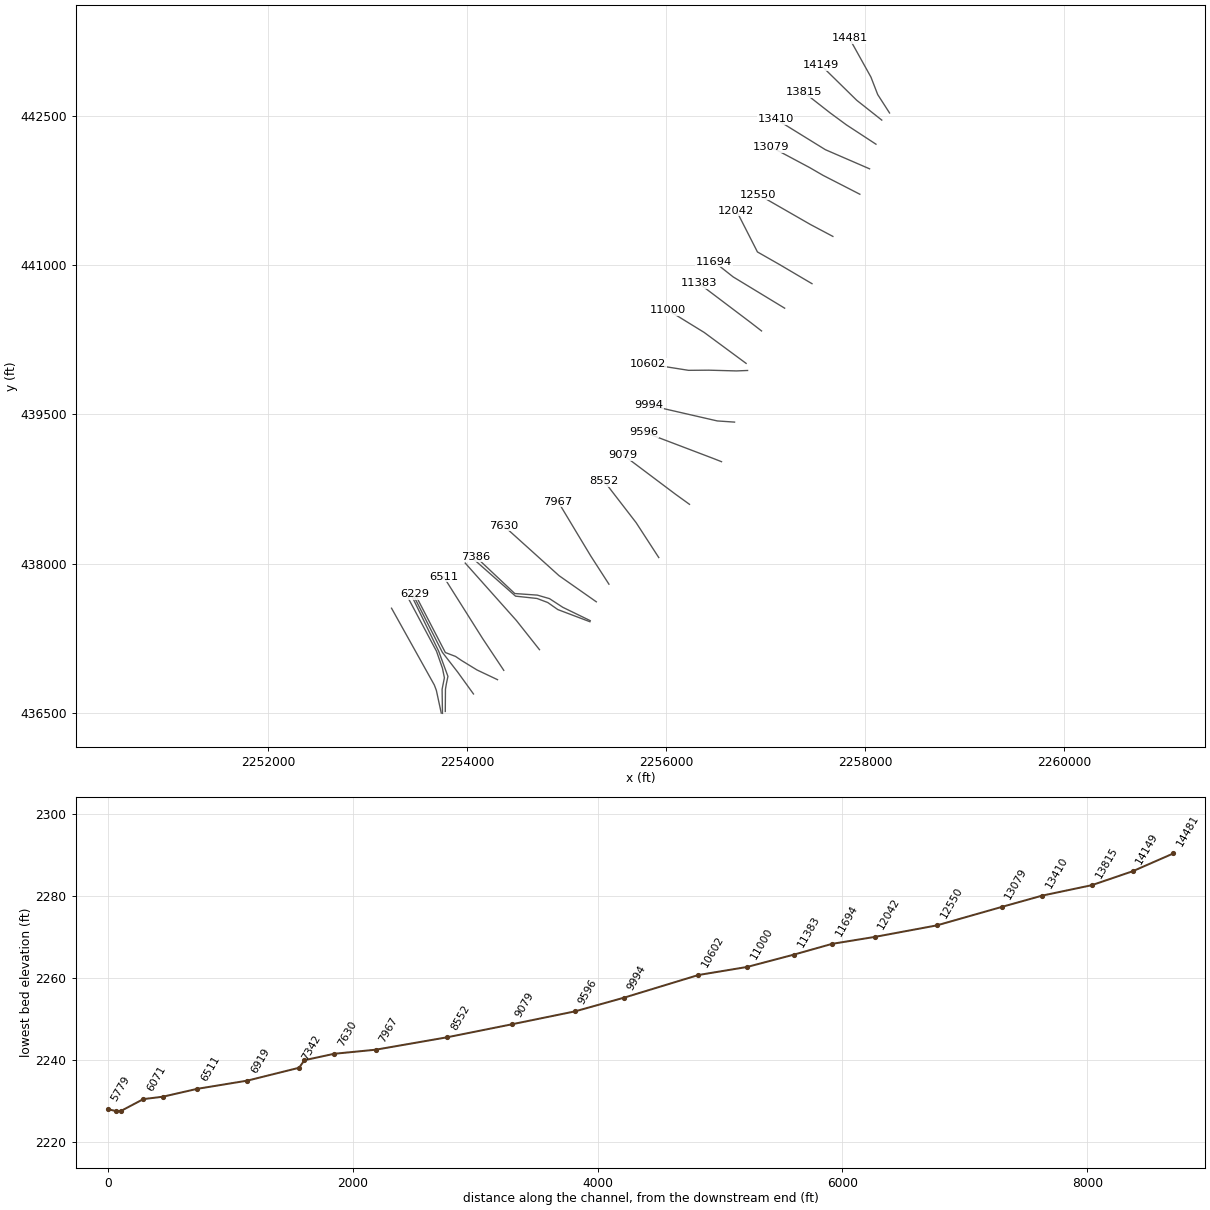
HEC-RAS study BRWNSCK.prj: BRWNSCK

--- BRWNSCK.g01 (geometry) --- (continued)

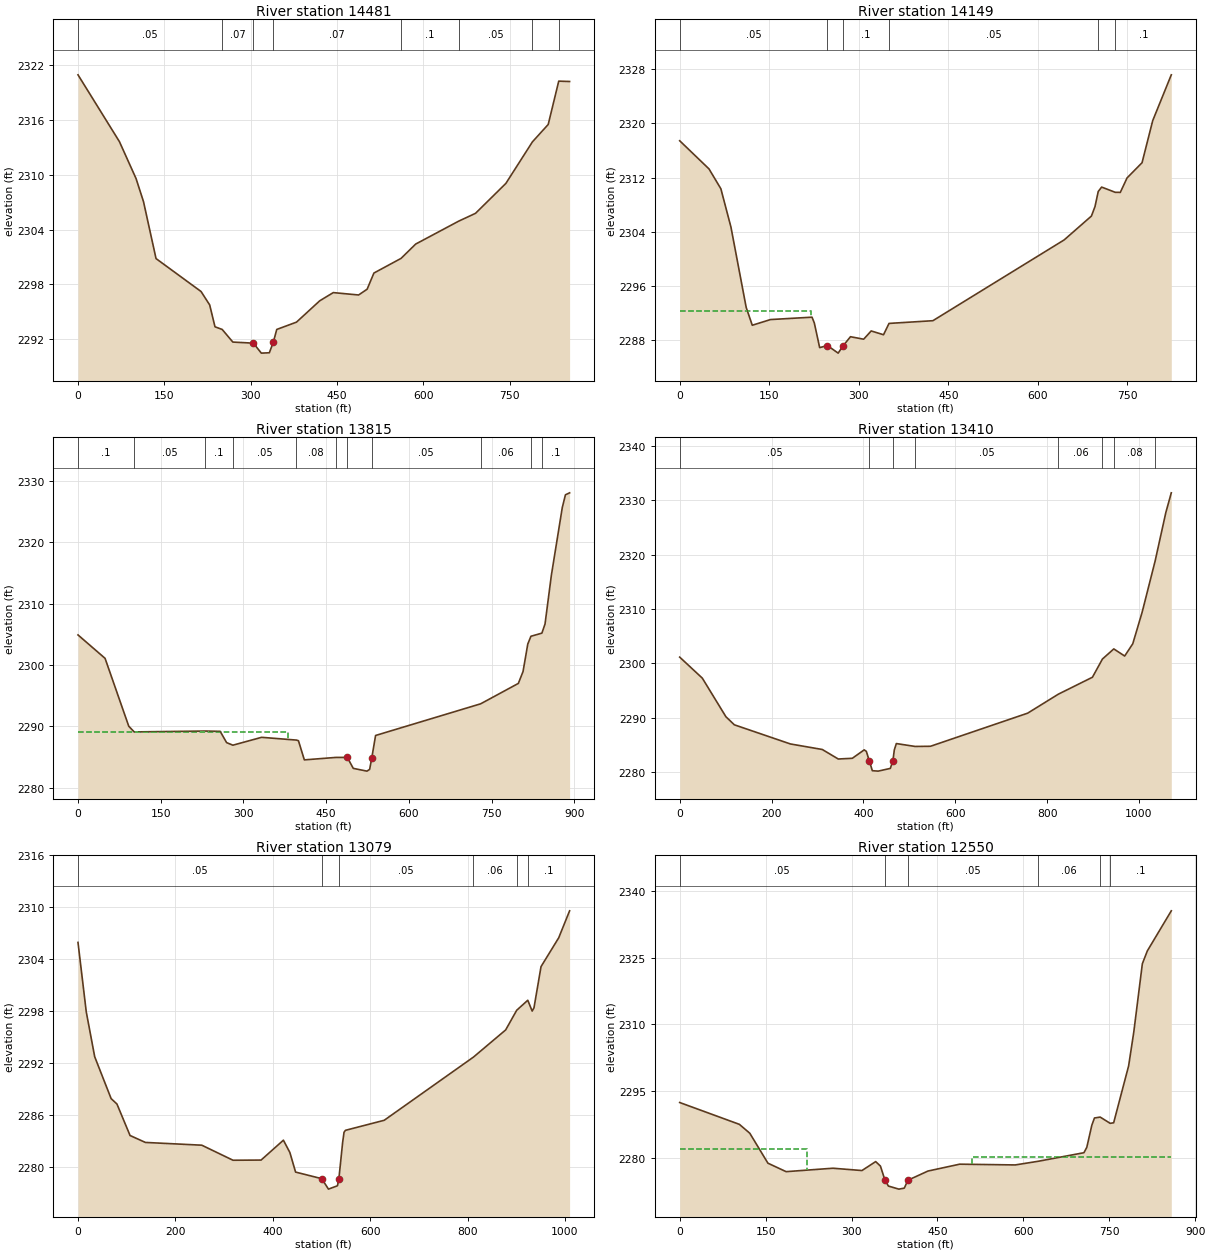
Type RM Length L Ch R = 1 ,14481   ,208,332.5,275.8
XS GIS Cut Line= 4
2258245.70238447442531.2658399542258126.69799346 442716.38378152
2258058.93160414442891.5846905032257842.40972606443281.654638805
#Sta/Elev= 30
       0 2320.92      72 2313.61   100.9 2309.57   113.8 2307.05   135.6 2300.82
   213.8 2297.22   228.8 2295.75     238 2293.36   250.5 2293.07     269 2291.69
   304.7 2291.57   318.5 2290.48   332.4 2290.52  339.28 2291.66   345.3 2293.07
   379.6 2293.87   419.9  2296.2   443.5  2297.1   487.5 2296.84   502.3 2297.47
   514.1 2299.24   561.2 2300.84   586.7 2302.41   661.2 2304.91   690.6 2305.77
   743.3 2309.04   789.5 2313.59   816.9 2315.49   835.2 2320.23854.0546 2320.19
#Mann= 8 ,-1,0
       0     .05       0   250.5     .07       0   304.7    .045       0
  339.28     .07       0   561.2      .1       0   661.2     .05       0
   789.5     .06       0   835.2    .016       0
Bank Sta=304.7,339.28
XS Rating Curve= 0 ,0
Exp/Cntr(USF)=0,0
Exp/Cntr=0.3,0.1

Type RM Length L Ch R = 1 ,14149   ,281.9,333.2,298.7
Node Name=D
XS GIS Cut Line= 3
2258167.54513596442459.638113385 2257915.9577371442658.720315956
2257557.17222917443010.942674352
#Sta/Elev= 30
       0 2317.44    49.1 2313.29      69 2310.36    85.9  2304.7   111.4 2292.87
   121.6 2290.24   152.2 2291.08   221.7 2291.43   225.6 2290.56   234.5 2286.94
   247.4 2287.25   265.5 2286.13   273.2 2287.14   286.1 2288.55   308.2 2288.18
   320.8  2289.4   341.5 2288.84   350.7 2290.51   424.2 2290.91   644.1 2302.82
   689.8 2306.34   695.8 2307.74   701.2 2309.96   706.9 2310.61   729.7 2309.84
   738.2 2309.83   749.5 2311.96   774.6  2314.2   792.5 2320.41823.6069 2327.16
#Mann= 6 ,-1,0
       0     .05       0   247.4    .045       0   273.2      .1       0
   350.7     .05       0   701.2    .016       0   729.7      .1       0
#XS Ineff= 2 , 0
          219.72 2292.37
Permanent Ineff=
       F       F
Bank Sta=247.4,273.2
XS Rating Curve= 0 ,0
Exp/Cntr(USF)=0,0
Exp/Cntr=0.3,0.1

Type RM Length L Ch R = 1 ,13815   ,331.5,405.3,391.1
XS GIS Cut Line= 4
2258109.23238588442217.1845090252257811.72140836  442412.0541993
2257648.09037072442532.5461451952257386.28071051442737.828719682
#Sta/Elev= 30
       0 2304.89    49.1 2301.08    92.1 2290.03   101.9 2289.11   230.8 2289.25
   257.9  2289.2   269.5 2287.37   280.9 2286.95     333 2288.23   396.2 2287.78
   399.8 2287.68   410.5 2284.56   467.7 2284.96  488.45 2284.96   499.2 2283.18
     524 2282.73   528.9 2283.01   532.9 2284.93   539.7 2288.53   730.2 2293.68
   798.6    2297   807.1 2298.93   815.7  2303.4   821.4 2304.67   841.3 2305.18
     847 2306.67   858.6 2314.66   878.3 2325.62     884 2327.69891.5518 2328.01
#Mann= 11 ,-1,0
       0      .1       0   101.9     .05       0   230.8      .1       0
   280.9     .05       0   396.2     .08       0   467.7     .05       0
  488.45    .045       0   532.9     .05       0   730.2     .06       0
   821.4    .016       0   841.3      .1       0
#XS Ineff= 2 , 0
          381.41 2289.17
Permanent Ineff=
       F       F
Bank Sta=488.45,532.9
XS Rating Curve= 0 ,0
Exp/Cntr(USF)=0,0
Exp/Cntr=0.3,0.1

Type RM Length L Ch R = 1 ,13410   ,320.1,331.4,250.2
XS GIS Cut Line= 3
 2258045.0330113441969.5896147482257600.92655941442162.108667784
2257102.12719472442470.576695944
#Sta/Elev= 30
       0 2301.15    49.3 2297.28   100.7 2290.18     119  2288.7     241 2285.18
   310.5 2284.16   345.3 2282.41   375.9 2282.54   401.8 2284.09   406.4 2283.82
  413.08 2282.03   419.5 2280.26   432.2 2280.18   458.7 2280.68   464.2 2282.05
   467.4  2284.1   471.8 2285.25   512.7 2284.72   546.1 2284.75   757.7 2290.84
   824.5 2294.33   898.8 2297.45   920.6  2300.8   945.3 2302.66     969 2301.35
   986.6  2303.6    1007  2309.4  1035.2 2318.79  1058.7 2327.771070.515 2331.37
#Mann= 8 ,-1,0
       0     .05       0  413.08    .045       0   464.2      .1       0
   512.7     .05       0   824.5     .06       0   920.6    .016       0
   945.3     .08       0  1035.2      .1       0
Bank Sta=413.08,464.2
XS Rating Curve= 0 ,0
Exp/Cntr(USF)=0,0
Exp/Cntr=0.3,0.1

Type RM Length L Ch R = 1 ,13079   ,523.3,529.2,519
XS GIS Cut Line= 4
2257947.31115742441714.1194984542257577.07527428441904.195956313
 2257443.1953344 441981.879378222257056.43106363442188.484223719
#Sta/Elev= 30
       0 2305.94      17  2297.9    34.3 2292.72      68 2287.88      80 2287.25
   106.9 2283.61   138.4 2282.81   254.2 2282.49   318.3 2280.75     376 2280.77
   421.8 2283.07   435.1 2281.64   446.8 2279.38   500.5 2278.62   514.3 2277.41
   532.8  2277.8  535.72 2278.62   543.4  2282.8   546.3 2283.99   549.2 2284.21
   628.8 2285.37   812.1 2292.68   878.2 2295.82   900.8 2298.09   923.6 2299.25
   932.6    2298   936.3 2298.37   950.8 2303.14   987.1 2306.471009.451 2309.59
#Mann= 6 ,-1,0
       0     .05       0   500.5    .045       0  535.72     .05       0
   812.1     .06       0   900.8    .016       0   923.6      .1       0
Bank Sta=500.5,535.72
XS Rating Curve= 0 ,0
Exp/Cntr(USF)=0,0
Exp/Cntr=0.3,0.1

Type RM Length L Ch R = 1 ,12550   ,512.9,508,507.4
XS GIS Cut Line= 3
2257676.26086659441290.1794445462257451.23257685441409.575180147
2256927.91933366441710.336048777
#Sta/Elev= 30
       0 2292.39   104.2 2287.48   122.4 2285.48   154.1 2278.74   185.8 2276.84
   267.5 2277.61   318.2 2277.09   342.2  2279.1   350.5 2278.09   358.3 2274.97
   364.4  2273.6   382.7 2272.91   392.1 2273.13  398.54 2274.92   433.6 2276.98
   488.9 2278.52   585.8 2278.35   625.8 2279.17   705.8  2281.1   710.8 2282.31
   719.6 2287.29   724.2 2288.91   734.2 2289.11   751.6 2287.71   757.7 2287.83
   783.8 2300.61   792.8  2308.2   807.8  2323.6   816.5 2326.49858.3254  2335.5
#Mann= 6 ,-1,0
       0     .05       0   358.3    .045       0  398.54     .05       0
   625.8     .06       0   734.2    .016       0   751.6      .1       0
#XS Ineff= 2 , 0
          222.59 2281.95  509.86          2280.2
Permanent Ineff=
       F       F
Bank Sta=358.3,398.54
XS Rating Curve= 0 ,0
Exp/Cntr(USF)=0,0
Exp/Cntr=0.3,0.1

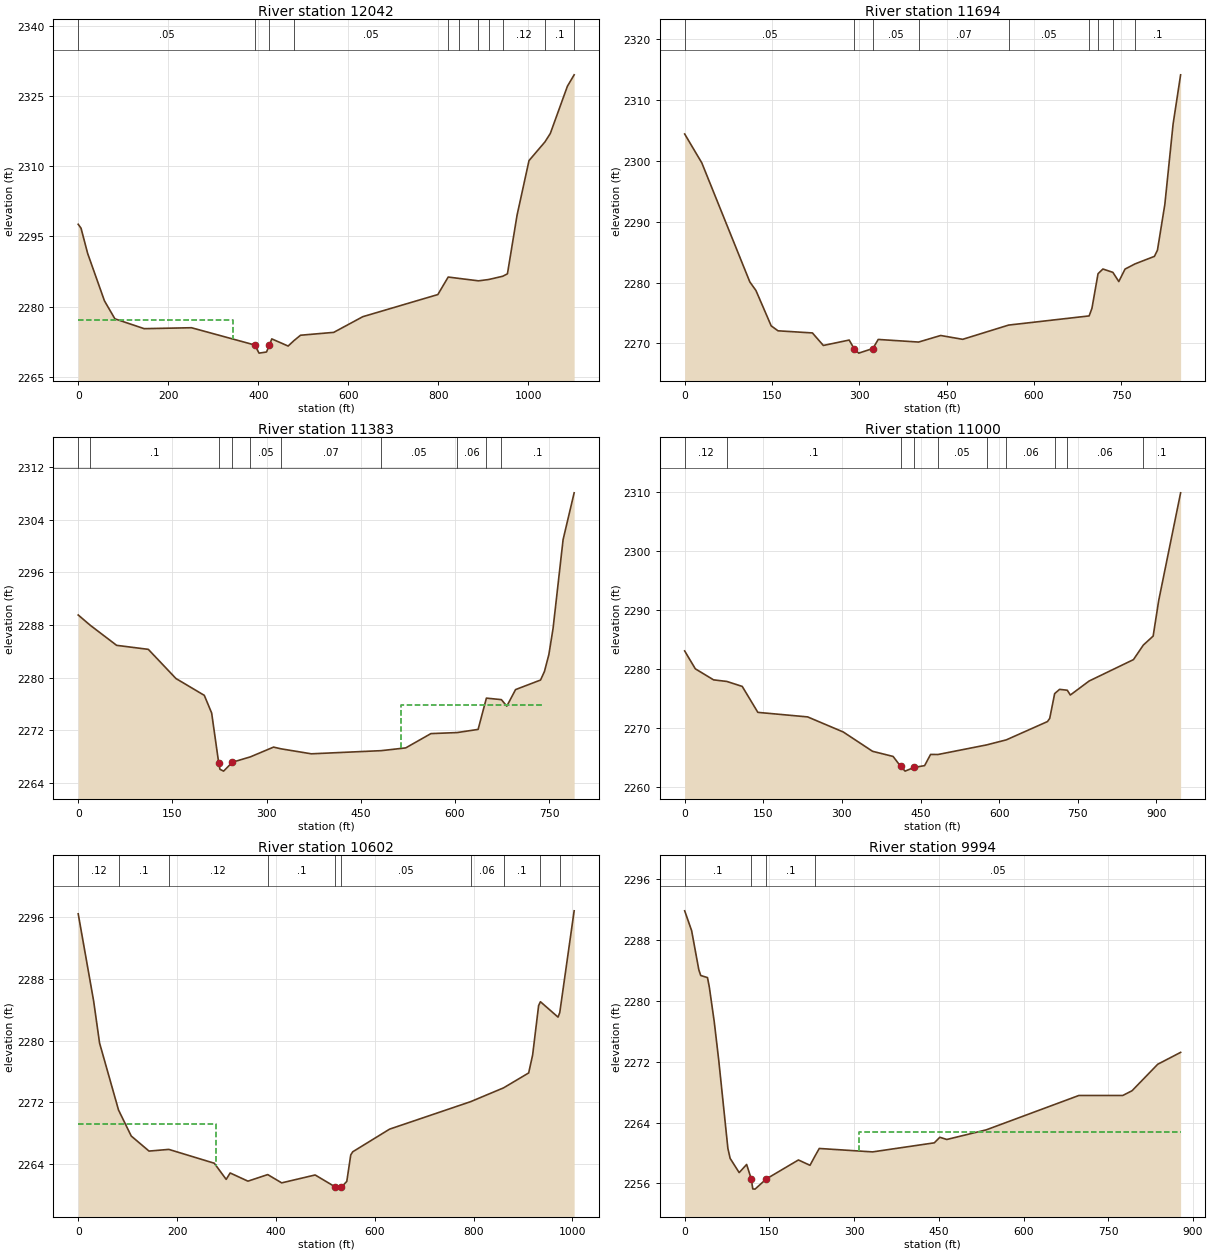
Type RM Length L Ch R = 1 ,12042   ,348.5,347.6,348.7
XS GIS Cut Line= 4
2257466.40102114440814.8201007952257139.67557433441007.549680575
2256918.35900773441133.8819072522256706.29949432441550.521686458
#Sta/Elev= 30
       0 2297.59     6.3 2296.75    20.9 2291.39    58.3 2281.25    81.5 2277.41
   146.6 2275.31   251.6 2275.51   391.9 2271.83   401.8 2270.09   418.3 2270.33
   424.8 2271.81     430 2273.13   466.3  2271.6   479.4 2272.77   493.9 2273.91
   567.6 2274.52   632.3 2277.87   798.9 2282.59   821.9 2286.33   846.5 2286.03
   889.2 2285.52   911.7  2285.8   943.1  2286.5   953.5 2287.02   974.9 2299.54
  1001.4 2311.18  1036.8 2315.17  1048.7 2316.96  1086.7 2327.05  1101.7 2329.49
#Mann= 11 ,-1,0
       0     .05       0   391.9    .045       0   424.8     .07       0
   479.4     .05       0   821.9    .016       0   846.5     .06       0
   889.2    .016       0   911.7     .06       0   943.1     .12       0
  1036.8      .1       0  1101.7     .12       0
#XS Ineff= 2 , 0
          342.76 2277.24
Permanent Ineff=
       F       F
Bank Sta=391.9,424.8
XS Rating Curve= 0 ,0
Exp/Cntr(USF)=0,0
Exp/Cntr=0.3,0.1

Type RM Length L Ch R = 1 ,11694   ,298.1,310.9,282.1
XS GIS Cut Line= 3
2257191.77469652440568.4141156512256674.41572331440882.860868198
2256480.91002944441036.052875849
#Sta/Elev= 30
       0 2304.43    29.4 2299.69   111.9 2280.12   122.5 2278.69   148.7 2272.88
   160.4 2272.07   219.5 2271.72   238.3 2269.66   282.7 2270.55   291.4 2269.08
   299.1  2268.4   323.4 2269.16   332.6 2270.65   401.9 2270.22   439.9  2271.3
   477.7 2270.67   556.6 2273.01     695 2274.52   699.8 2275.76   710.3 2281.46
   718.7 2282.23   735.8 2281.68     746 2280.17   756.7 2282.22   773.8 2283.07
   807.2 2284.31   812.4 2285.33   825.1 2292.86   839.3 2306.08   852.2 2314.16
#Mann= 9 ,-1,0
       0     .05       0   291.4    .045       0   323.4     .05       0
   401.9     .07       0   556.6     .05       0     695     .06       0
   710.3    .016       0   735.8     .06       0   773.8      .1       0
Bank Sta=291.4,323.4
XS Rating Curve= 0 ,0
Exp/Cntr(USF)=0,0
Exp/Cntr=0.3,0.1

Type RM Length L Ch R = 1 ,11383   ,372.4,382.9,363.6
XS GIS Cut Line= 3
2256959.41282892440339.6929030612256846.43884557440427.136674941
 2256330.1315423440817.480898563
#Sta/Elev= 30
       0  2289.5    19.3 2287.93    61.2 2284.89   111.7 2284.28   155.7 2279.85
   200.9 2277.29   212.6 2274.61   223.82267.046   225.8 2266.06   231.6 2265.78
   245.72267.132   274.4 2267.95   311.2 2269.43     323 2269.17   371.4 2268.41
   482.9 2268.89   521.8 2269.31   561.9 2271.48   603.9 2271.64   637.1 2272.12
   650.3 2276.87   674.2 2276.64   682.8 2275.65   696.8 2278.17   736.6 2279.62
   742.8 2280.93   749.8 2283.48   756.5 2287.45   772.5 2300.96   790.1 2308.06
#Mann= 10 ,-1,0
       0     .05       0    19.3      .1       0   223.8    .045       0
   245.7      .1       0   274.4     .05       0     323     .07       0
   482.9     .05       0   603.9     .06       0   650.3    .016       0
   674.2      .1       0
#XS Ineff= 1 ,-1
  514.71   741.22275.896
Permanent Ineff=
       F
Bank Sta=223.8,245.7
XS Rating Curve= 0 ,0
Exp/Cntr(USF)=0,0
Exp/Cntr=0.3,0.1

Type RM Length L Ch R = 1 ,11000   ,311.5,398.4,403.9
Node Name=C
XS GIS Cut Line= 3
  2256804.497828440013.4249725152256383.51979482440324.323944021
2256023.53151202440545.969622272
#Sta/Elev= 30
       0 2283.13    20.3  2280.1    55.1 2278.23    80.4 2277.96   109.8 2277.12
   139.6 2272.72   234.6 2271.95   302.6 2269.39   358.4 2266.12   397.6 2265.25
   411.9 2263.58   420.5 2262.76   437.7 2263.39   457.7 2263.69   469.1 2265.59
   483.4 2265.58   575.8  2267.2   613.6 2268.06   692.1 2271.16   696.4 2271.71
   705.8  2275.9   715.2 2276.62   729.9 2276.47   735.7 2275.66   771.5 2278.03
   856.1 2281.66   874.9 2284.12   893.7 2285.65   904.3 2291.68 946.087 2309.93
#Mann= 10 ,-1,0
       0     .12       0    80.4      .1       0   411.9    .045       0
   437.7      .1       0   483.4     .05       0   575.8     .05       0
   613.6     .06       0   705.8    .016       0   729.9     .06       0
   874.9      .1       0
Bank Sta=411.9,437.7
XS Rating Curve= 0 ,0
Exp/Cntr(USF)=0,0
Exp/Cntr=0.3,0.1

Type RM Length L Ch R = 1 ,10602   ,536.1,608,549.3
XS GIS Cut Line= 5
2256819.37337688439942.0223379112256706.31920542439937.559673249
2256431.12155122439944.9974476872256225.83897673439943.509892799
 2255821.2240473440007.474752965
#Sta/Elev= 30
       0  2296.4    31.2 2285.13    43.2 2279.69    81.6 2271.02   107.3 2267.66
   143.3 2265.71   183.3 2265.93   275.3 2264.14   299.4 2262.05   307.4 2262.88
   343.4 2261.82   383.4 2262.67   411.7  2261.6   479.4 2262.62   519.4  2261.1
   527.4 2260.79   532.6 2261.06   543.4 2261.79   551.4 2265.21   555.4 2265.62
     630 2268.55   793.8  2272.1   860.6 2273.89   911.4 2275.82   919.4 2278.14
   931.5 2284.53   935.2 2285.03   970.8 2283.04   974.3 2283.63  1003.4 2296.79
#Mann= 10 ,-1,0
       0     .12       0    81.6      .1       0   183.3     .12       0
   383.4      .1       0   519.4    .045       0   532.6     .05       0
   793.8     .06       0   860.6      .1       0   935.2    .016       0
   974.3     .07       0
#XS Ineff= 2 , 0
          279.07 2269.17
Permanent Ineff=
       F       F
Bank Sta=519.4,532.6
XS Rating Curve= 0 ,0
Exp/Cntr(USF)=0,0
Exp/Cntr=0.3,0.1

Type RM Length L Ch R = 1 ,9994    ,401.7,397.3,369
XS GIS Cut Line= 3
2256688.46854677439422.8656821432256514.42462492439434.766121244
2255828.66182174439592.446939328
#Sta/Elev= 30
       0  2291.8    12.3  2289.2      25 2284.07    28.4 2283.31    40.4 2283.03
    43.7 2281.76    52.4  2277.2    60.4 2272.12    76.5  2260.6    80.5 2259.29
    96.5 2257.42   109.7 2258.49  117.81 2256.61   120.6 2255.28   124.6 2255.25
   144.6 2256.59   201.4 2259.08   221.9 2258.38   230.1 2259.51   238.3 2260.59
   332.7 2260.14     442 2261.33   451.8 2262.06   464.1 2261.77   533.8 2263.03
     698 2267.55   775.7 2267.55   792.1 2268.17   837.6 2271.65878.1078 2273.21
#Mann= 4 ,-1,0
       0      .1       0  117.81    .045       0   144.6      .1       0
   230.1     .05       0
#XS Ineff= 2 , 0
                          308.17         2262.79
Permanent Ineff=
       F       F
Bank Sta=117.81,144.6
XS Rating Curve= 0 ,0
Exp/Cntr(USF)=0,0
Exp/Cntr=0.3,0.1

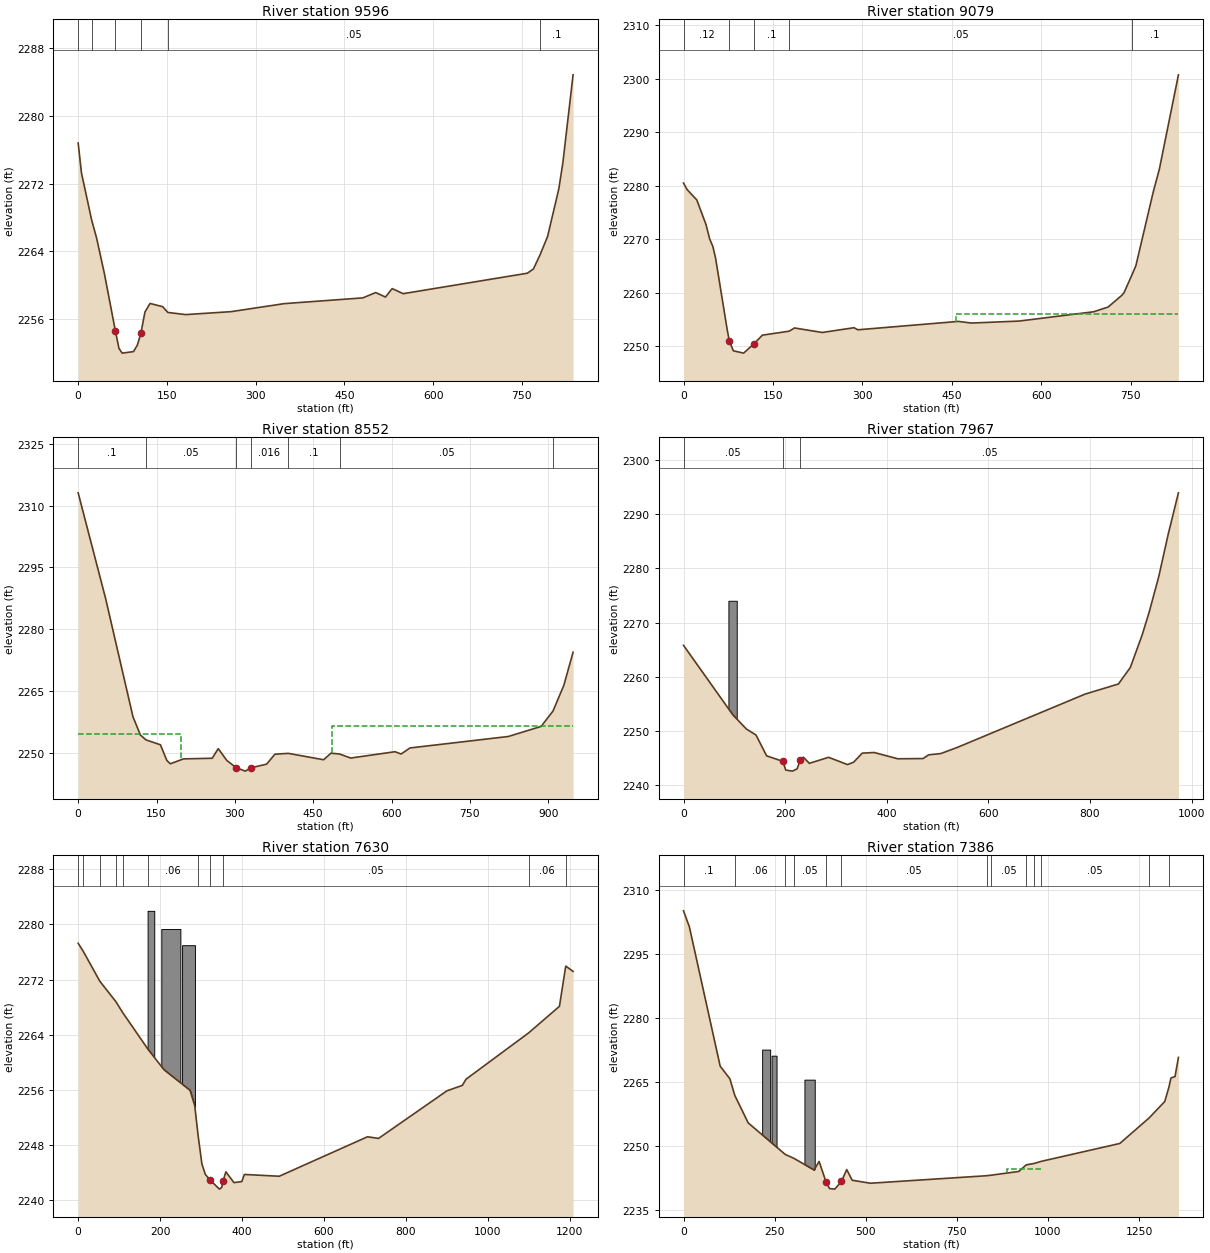
Type RM Length L Ch R = 1 ,9596    ,523.8,517.7,487.6
XS GIS Cut Line= 3
2256557.38578329439024.9231899042256473.99455884439057.697606571
2255775.90424047439323.441878966
#Sta/Elev= 30
       0 2276.81     5.6 2273.26    22.7 2267.72    31.4 2265.49    44.3 2261.36
    62.8  2254.6      69 2252.48    74.4 2251.93    93.6 2252.11   100.1 2252.89
   106.1  2254.3   112.9  2256.8   121.5 2257.81   142.9 2257.43   151.5 2256.75
   181.4 2256.49   258.5 2256.84   348.3 2257.79   481.2 2258.47   502.9  2259.1
   519.5 2258.57   530.8 2259.57   549.4 2258.97   759.2 2261.39   769.5 2261.89
   780.6 2263.54   793.5 2265.74   812.4 2271.35   819.2 2274.39   836.6 2284.88
#Mann= 6 ,-1,0
       0     .12       0    22.7      .1       0    62.8    .045       0
   106.1      .1       0   151.5     .05       0   780.6      .1       0
Bank Sta=62.8,106.1
XS Rating Curve= 0 ,0
Exp/Cntr(USF)=0,0
Exp/Cntr=0.3,0.1

Type RM Length L Ch R = 1 ,9079    ,541.6,526.6,494.9
XS GIS Cut Line= 3
2256235.79145606438596.1307535972256092.83602743438699.316809809
2255570.67156714439092.024481582
#Sta/Elev= 30
       0 2280.54     6.2  2279.3    22.3 2277.39    37.7 2272.79    43.9 2270.09
    49.2 2268.69    53.8  2266.5    73.5 2252.98      77 2250.98    83.6 2249.19
   100.8 2248.76     118  2250.5   132.3 2252.12   177.1 2252.86   186.1 2253.46
   232.6 2252.62   285.9 2253.51   292.2 2253.12   460.9 2254.69   482.4 2254.38
   562.5 2254.75   687.6 2256.49   711.8 2257.37   735.1 2259.59   738.4 2260.03
   751.7 2263.36   758.4 2265.11   787.7 2278.98   797.8 2283.17   829.7 2300.77
#Mann= 5 ,-1,0
       0     .12       0      77    .045       0     118      .1       0
   177.1     .05       0   751.7      .1       0
#XS Ineff= 2 , 0
                          457.46         2256.09
Permanent Ineff=
       F       F
Bank Sta=77,118
XS Rating Curve= 0 ,0
Exp/Cntr(USF)=0,0
Exp/Cntr=0.3,0.1

Type RM Length L Ch R = 1 ,8552    ,568.3,584.7,567.6
XS GIS Cut Line= 3
2255926.91581647438061.0481791812255699.73273464438411.490128503
2255376.28043578438831.227317827
#Sta/Elev= 30
       0 2313.09    52.6 2287.44     105 2258.75   119.3 2254.33     130 2253.17
   157.5 2251.99   169.8 2248.18   176.5 2247.38   201.6 2248.57   256.6 2248.72
   268.2 2251.06   284.5  2248.2   302.9  2246.4   320.2  2245.6     330 2246.38
   360.7 2247.29   376.7  2249.7   402.1 2249.91   469.9 2248.36   484.1 2249.96
   500.6 2249.74   521.8 2248.77   606.6 2250.31   618.2 2249.75   635.3 2251.22
   823.5    2254   886.3 2256.44   909.1 2260.18   929.8 2266.41   947.5 2274.44
#Mann= 7 ,-1,0
       0      .1       0     130     .05       0   302.9    .045       0
     330    .016       0   402.1      .1       0   500.6     .05       0
   909.1      .1       0
#XS Ineff= 2 , 0
          197.67 2254.63  486.71         2256.59
Permanent Ineff=
       F       F
Bank Sta=302.9,330
XS Rating Curve= 0 ,0
Exp/Cntr(USF)=0,0
Exp/Cntr=0.3,0.1

Type RM Length L Ch R = 1 ,7967    ,326.2,337.9,361.9
XS GIS Cut Line= 4
2255426.33634671437793.2387937772255245.00112779438074.571053603
2255111.30516901438296.413591485 2254915.6077005438622.508605021
#Sta/Elev= 30
       0 2265.79      97 2252.97   123.7 2250.34   142.7 2249.23   163.6 2245.38
   195.4 2244.37   201.2 2242.76   214.1 2242.56   223.6 2242.98   230.1 2244.68
   235.9 2245.13   247.6    2244   285.5 2245.11   322.7 2243.77   334.7  2244.2
   351.8 2245.88   375.2    2246   421.7 2244.84   471.3 2244.88   482.5 2245.57
   506.2  2245.8   538.6 2246.93   790.5 2256.79   855.9 2258.65   879.4 2261.71
   902.5 2267.67   916.5 2271.94   935.2 2278.44   953.8 2286.27     974 2293.95
#Mann= 3 ,-1,0
       0     .05       0   195.4    .045       0   230.1     .05       0
#Block Obstruct= 1 ,-1
   88.36  104.74 2274.02
Bank Sta=195.4,230.1
XS Rating Curve= 0 ,0
Exp/Cntr(USF)=0,0
Exp/Cntr=0.3,0.1

Type RM Length L Ch R = 1 ,7630    ,242.1,243.7,265
Node Name=B
XS GIS Cut Line= 3
2255299.44878902437616.0337563242254925.34926551437878.559737736
2254367.48155501438381.734535444
#Sta/Elev= 30
       0 2277.26    11.8 2276.16    52.9 2271.75      92 2268.79   109.4 2267.14
   170.1 2261.91   209.2 2258.93   273.1 2255.92   284.6 2253.69   293.2 2249.18
   302.1 2245.23   310.4 2243.72   321.9  2242.9   344.9 2241.57   350.6 2241.82
   353.5 2242.73   360.7 2244.08   380.3 2242.52   399.4 2242.66   405.9  2243.7
   490.9 2243.44   706.4 2249.17   733.3 2248.93   900.3 2255.84     938 2256.63
   946.8 2257.52  1099.6 2264.24    1175 2268.11  1190.4 2273.95 1208.29 2273.18
#Mann= 11 ,-1,0
       0    .016       0    11.8     .06       0    52.9     .05       0
      92    .016       0   109.4     .05       0   170.1     .06       0
   293.2     .05       0   321.9    .045       0   353.5     .05       0
  1099.6     .06       0  1190.4    .016       0
#Block Obstruct= 3 ,-1
  169.46   185.8 2281.97  202.97  249.57 2279.33  253.71  285.07 2276.98
Bank Sta=321.9,353.5
XS Rating Curve= 0 ,0
Exp/Cntr(USF)=0,0
Exp/Cntr=0.5,0.3

Type RM Length L Ch R = 1 ,7386    ,44.8,44.1,40.8
XS GIS Cut Line= 6
 2255238.6262561437426.3455081912254962.18639767437561.021336656
2254829.28261958437647.8518050082254707.01114374437683.292812499
 2254480.1886958 437699.241265872254089.59378979438067.608972122
#Sta/Elev= 30
       0 2305.17    16.1 2301.42   100.6  2268.8   127.3 2265.82   140.7 2261.95
   177.5 2255.51   279.2 2248.12   303.1  2247.2   358.2 2244.49     372 2246.49
   391.1 2241.67   400.7 2240.13     415    2240   433.3 2241.79   447.8 2244.58
   462.8 2242.08   512.8 2241.38     832 2243.14     843 2243.25   919.9 2244.14
   940.4 2245.69     961 2245.99   981.2  2246.5  1196.9 2250.69  1277.3 2256.66
  1320.3 2260.52  1331.7 2263.87  1337.3 2266.03  1348.5 2266.36  1357.8 2270.84
#Mann= 13 ,-1,0
       0      .1       0   140.7     .06       0   279.2    .016       0
   303.1     .05       0   391.1    .045       0   433.3     .05       0
     832     .06       0     843     .05       0   940.4    .016       0
     961     .06       0   981.2     .05       0  1277.3     .07       0
  1331.7    .016       0
#XS Ineff= 4 ,-1
       0     372 2243.98     443  886.49 2242.62  886.49  979.58 2244.72
  979.58  1357.8 2242.62
Permanent Ineff=
       F       F       F       F
#Block Obstruct= 3 ,-1
  215.74  237.72 2272.68  241.62  255.24 2271.25  331.75  360.02 2265.64
Bank Sta=391.1,433.3
XS Rating Curve= 0 ,0
Exp/Cntr(USF)=0,0
Exp/Cntr=0.5,0.3

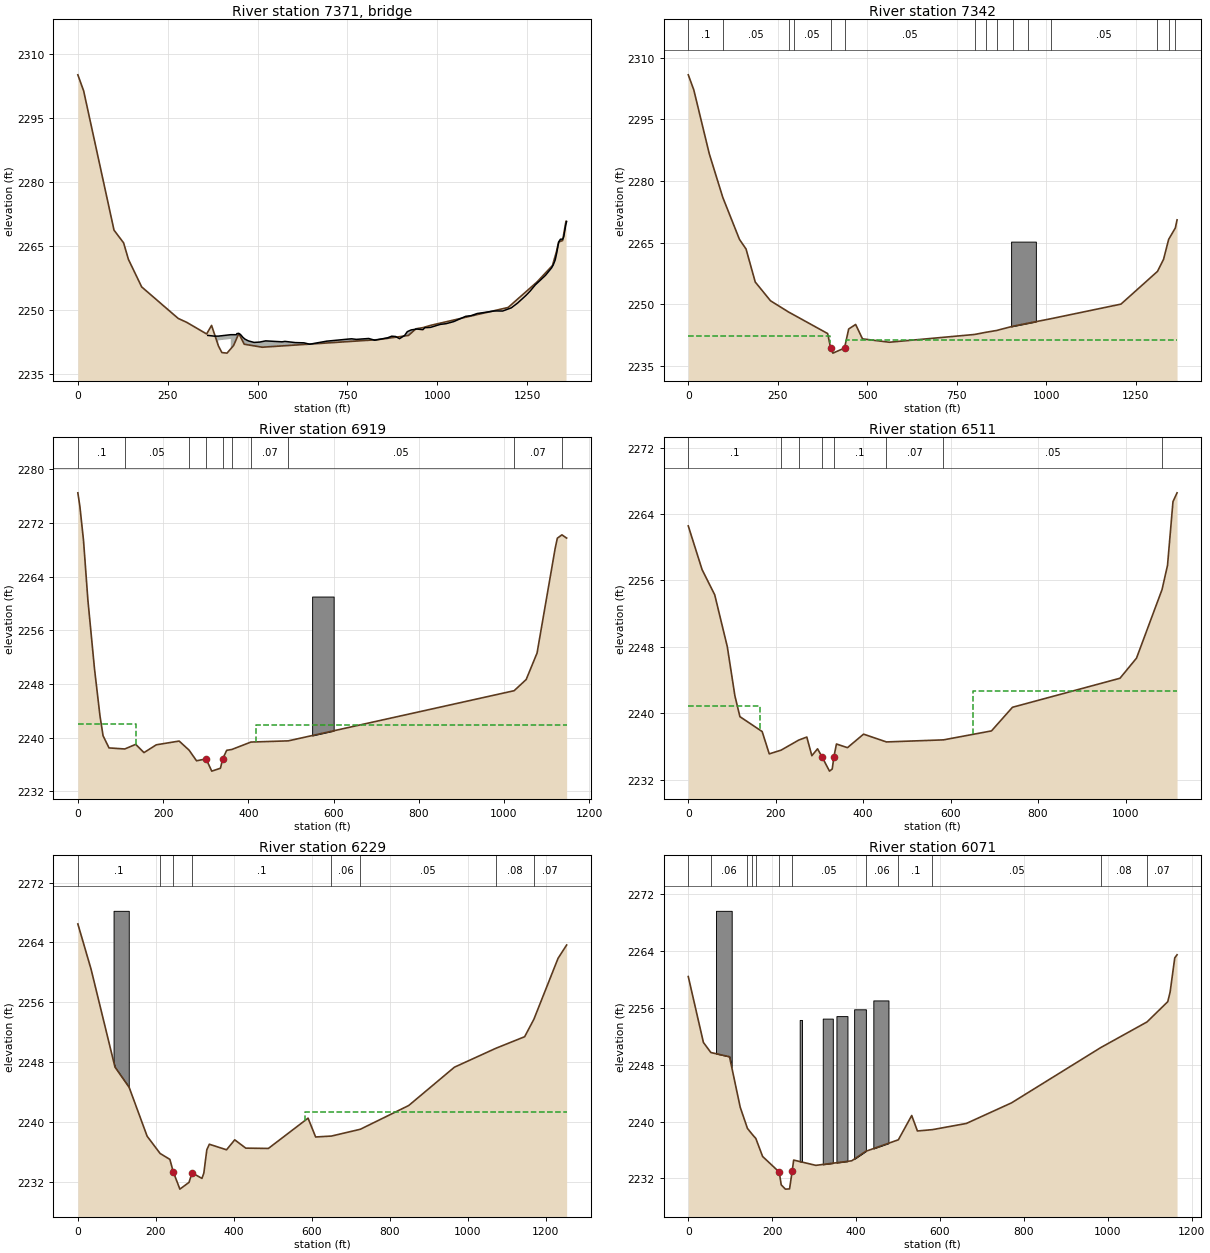
Type RM Length L Ch R = 3 ,7371    ,,,
BEGIN DESCRIPTION:
Unnamed Road
Missing survey because owner denied access.
Bridge opened determined by imagery
END DESCRIPTION:
Bridge Culvert--1,0,-1,-1, 0
Deck Dist Width WeirC Skew NumUp NumDn MinLoCord MaxHiCord MaxSubmerge Is_Ogee
18.08003,10,2.6,0, 60, 60, , , 0.98, 0, 0,0,,
   361.3   379.6   390.5   425.5   441.2   442.5   447.3   452.1   459.2     465
   474.3   490.1   505.9   522.4   567.9   576.3   604.8   628.9     645     692
   761.2   774.7   809.1   825.9   861.6   873.1     884   894.8   909.1   916.4
   927.3   943.5   959.7   965.1   980.9  1008.4  1024.7    1046  1078.8  1094.1
  1110.9    1160  1181.9  1205.9  1223.8  1247.5  1258.4  1272.5  1300.7  1317.8
  1322.4  1327.8    1332  1336.6  1338.6  1342.5    1349  1351.8  1357.5  1359.7
 2244.15 2243.98 2243.98 2244.32 2244.32 2244.58 2244.62 2244.39 2243.69 2243.27
 2242.87 2242.51 2242.59 2242.87 2242.65 2242.75 2242.47 2242.41 2242.09  2242.8
 2243.36 2243.22 2243.43 2243.02 2243.59 2243.97 2243.89 2243.38 2244.15 2245.03
 2245.44 2245.64 2245.49 2245.95 2246.03 2246.73  2246.9 2247.39 2248.62 2248.78
 2249.28 2249.88 2249.86 2250.61 2251.76 2253.59 2254.55 2255.98  2258.2 2259.96
 2260.65  2261.8  2263.4 2265.52 2266.17 2266.68 2266.69 2267.27 2270.12 2270.83
                 2242.98 2243.32
                                                                                
                                                                                
                                                                                
                                                                                
                                                                                
   361.3   379.6   400.5   435.5   441.2   442.5   447.3   452.1   459.2     465
   474.3   490.1   505.9   522.4   567.9   576.3   604.8   628.9     645     692
   761.2   774.7   809.1   825.9   861.6   873.1     884   894.8   909.1   916.4
   927.3   943.5   959.7   965.1   980.9  1008.4  1024.7    1046  1078.8  1094.1
  1110.9    1160  1181.9  1205.9  1223.8  1247.5  1258.4  1272.5  1300.7  1317.8
  1322.4  1327.8    1332  1336.6  1338.6  1342.5    1349  1351.8  1357.5  1359.7
 2244.15 2243.98 2243.98 2244.32 2244.32 2244.58 2244.62 2244.39 2243.69 2243.27
 2242.87 2242.51 2242.59 2242.87 2242.65 2242.75 2242.47 2242.41 2242.09  2242.8
 2243.36 2243.22 2243.43 2243.02 2243.59 2243.97 2243.89 2243.38 2244.15 2245.03
 2245.44 2245.64 2245.49 2245.95 2246.03 2246.73  2246.9 2247.39 2248.62 2248.78
 2249.28 2249.88 2249.86 2250.61 2251.76 2253.59 2254.55 2255.98  2258.2 2259.96
 2260.65  2261.8  2263.4 2265.52 2266.17 2266.68 2266.69 2267.27 2270.12 2270.83
                 2242.98 2243.32
                                                                                
                                                                                
                                                                                
                                                                                
                                                                                
BR Coef=-1 ,-1 , 0 ,, 0 ,,,0.8,0,1.2,0,
WSPro=,,,, 1 ,,,, 0 ,,,, 0 ,,,,-1 ,-1 ,-1 , 0 , 0 , 0 , 0 , 0
BR U #Sta/Elev= 30
       0 2305.17    16.1 2301.42   100.6  2268.8   127.3 2265.82   140.7 2261.95
   177.5 2255.51   279.2 2248.12   303.1  2247.2   358.2 2244.49     372 2246.49
   391.1 2241.67   400.7 2240.13     415    2240   433.3 2241.79   447.8 2244.58
   462.8 2242.08   512.8 2241.38     832 2243.14     843 2243.25   919.9 2244.14
   940.4 2245.69     961 2245.99   981.2  2246.5  1196.9 2250.69  1277.3 2256.66
  1320.3 2260.52  1331.7 2263.87  1337.3 2266.03  1348.5 2266.36  1357.8 2270.84
BR U #Mann= 13
       0      .1   140.7     .06   279.2    .016   303.1     .05   391.1     .04
   433.3     .05     832     .06     843     .05   940.4    .016     961     .06
   981.2     .05  1277.3     .07  1331.7    .016
BR D #Sta/Elev= 30
       0 2305.85    15.4  2302.2    58.7 2286.64    96.4 2276.04     143 2265.82
   161.4 2263.48   187.1 2255.45   229.8 2250.88   281.2  2248.1     294 2247.49
   389.4 2242.91  397.52 2239.48     404 2238.15   436.5 2239.38   448.1 2244.02
   467.6 2245.12   486.7 2241.62   561.7  2240.8     800 2242.69   831.4 2243.22
 861.3252243.657     907  2244.7   949.8 2245.44  1012.6 2246.51  1208.8 2250.07
  1310.8 2258.03  1327.8 2260.98    1342 2265.81  1360.8 2268.62  1365.5 2270.57
BR D #Mann= 15
       0      .1    96.4     .05   281.2     .06     294     .05  397.52     .04
   436.5     .05     800    .016   831.4     .06 861.325     .05     907    .016
   949.8     .06  1012.6     .05  1310.8     .07    1342     .06  1360.8    .016
BC Design=,, 0 ,, 0 ,,,,,,
BC Use User HTab Curves=0
BC User HTab FreeFlow(D)= 0

Type RM Length L Ch R = 1 ,7342    ,389.6,422.6,327.4
XS GIS Cut Line= 6
2255235.08215535437415.7132059442254912.56898718437537.984681787
2254811.56211584437608.8666967682254703.46704299437649.623855383
2254487.80596316 437672.914385632254064.58819006 438046.86941959
#Sta/Elev= 30
       0 2305.85    15.4  2302.2    58.7 2286.64    96.4 2276.04     143 2265.82
   161.4 2263.48   187.1 2255.45   229.8 2250.88   281.2  2248.1     294 2247.49
   389.4 2242.91  397.52 2239.48     404 2238.15   436.5 2239.38   448.1 2244.02
   467.6 2245.12   486.7 2241.62   561.7  2240.8     800 2242.69   831.4 2243.22
861.32482243.657     907  2244.7   949.8 2245.44  1012.6 2246.51  1208.8 2250.07
  1310.8 2258.03  1327.8 2260.98    1342 2265.81  1360.8 2268.62  1365.5 2270.57
#Mann= 15 ,-1,0
       0      .1       0    96.4     .05       0   281.2     .06       0
     294     .05       0  397.52    .045       0   436.5     .05       0
     800    .016       0   831.4     .06       0861.3248     .05       0
     907    .016       0   949.8     .06       0  1012.6     .05       0
  1310.8     .07       0    1342     .06       0  1360.8    .016       0
#XS Ineff= 2 , 0
             395  2242.4     440          2241.4
Permanent Ineff=
       F       F
#Block Obstruct= 1 ,-1
  901.89  971.06 2265.28
Bank Sta=397.52,436.5
XS Rating Curve= 0 ,0
Exp/Cntr(USF)=0,0
Exp/Cntr=0.5,0.3

Type RM Length L Ch R = 1 ,6919    ,411.2,408.3,383.7
XS GIS Cut Line= 3
2254728.45477945437134.736123734 2254496.5568292437427.890136311
2253982.44344894438005.447295419
#Sta/Elev= 30
       0 2276.47     4.8 2274.43    13.3 2269.37    23.5 2260.54    39.1 2250.23
      52  2243.2    59.2 2240.28    73.1 2238.47   110.2 2238.31   135.8    2239
   155.2 2237.77   184.1 2238.93   237.7 2239.49   261.1 2238.13   278.5 2236.55
   300.9 2236.83   314.2 2235.01   334.6 2235.44  339.92 2236.85   349.3 2238.11
   361.5 2238.24   406.1 2239.34     494 2239.52  1023.8 2246.99  1052.1 2248.66
  1077.6  2252.6  1120.1 2268.19  1125.2 2269.71  1135.9 2270.211147.016 2269.73
#Mann= 10 ,-1,0
       0      .1       0   110.2     .05       0   261.1      .1       0
   300.9    .045       0  339.92      .1       0   361.5     .05       0
   406.1     .07       0     494     .05       0  1023.8     .07       0
  1135.9    .016       0
#XS Ineff= 2 , 0
          136.56    2242   417.8         2241.87
Permanent Ineff=
       F       F
#Block Obstruct= 1 ,-1
  549.79  600.26 2261.02
Bank Sta=300.9,339.92
XS Rating Curve= 0 ,0
Exp/Cntr(USF)=0,0
Exp/Cntr=0.3,0.1

Type RM Length L Ch R = 1 ,6511    ,230.5,282.2,318.2
XS GIS Cut Line= 3
2254369.66927152436926.9030551162254157.46076988437246.309665834
2253765.85951427437867.621155177
#Sta/Elev= 30
       0 2262.58    31.6 2257.31    60.5 2254.27    89.3 2248.01   106.6  2242.1
   118.1 2239.58     169 2237.78   185.2 2235.09   212.3 2235.54   252.5 2236.75
   271.1 2237.12   282.6 2234.87   295.7  2235.7   306.3 2234.69     323 2233.01
   329.3 2233.27  332.89 2234.69   338.9 2236.28   364.1 2235.84   400.9 2237.47
   453.2 2236.53   583.7 2236.78   693.5 2237.86   741.5 2240.71   987.4 2244.21
  1025.2 2246.64  1083.6 2254.91  1096.1 2257.83  1108.6 2265.51  1117.9 2266.57
#Mann= 8 ,-1,0
       0      .1       0   212.3     .07       0   252.5      .1       0
   306.3    .045       0  332.89      .1       0   453.2     .07       0
   583.7     .05       0  1083.6     .06       0
#XS Ineff= 2 , 0
          162.93  2240.9  651.72         2242.71
Permanent Ineff=
       F       F
Bank Sta=306.3,332.89
XS Rating Curve= 0 ,0
Exp/Cntr(USF)=0,0
Exp/Cntr=0.3,0.1

Type RM Length L Ch R = 1 ,6229    ,170.2,158.1,88.3
XS GIS Cut Line= 6
2254306.81922371436833.0629932672254100.64411629436930.795349381
2253944.86281595437026.3090404382253885.09741308437066.864135242
2253782.64243673437105.9962442652253478.52010416437692.754005479
#Sta/Elev= 30
       0 2266.47    33.9 2260.43    95.2 2247.37   131.6 2244.66   177.7 2238.14
     211 2235.84     236 2235.05   244.7 2233.39   261.7 2231.08   285.1 2231.98
     293 2233.25   318.3 2232.51   323.1 2233.21   330.8 2236.33   337.2 2237.07
   381.4 2236.33   402.4 2237.66   430.7 2236.55   488.7 2236.51   590.5 2240.55
   609.9 2238.04   650.3 2238.16   724.6 2239.07   848.7 2242.24   965.8 2247.35
  1071.5 2249.86    1146 2251.42  1169.7 2253.75  1231.7 2261.88  1253.7 2263.66
#Mann= 8 ,-1,0
       0      .1       0     211     .07       0   244.7    .045       0
     293      .1       0   650.3     .06       0   724.6     .05       0
  1071.5     .08       0  1169.7     .07       0
#XS Ineff= 2 , 0
                          582.18         2241.35
Permanent Ineff=
       F       F
#Block Obstruct= 1 ,-1
    91.6  130.58 2268.22
Bank Sta=244.7,293
XS Rating Curve= 0 ,0
Exp/Cntr(USF)=0,0
Exp/Cntr=0.3,0.1

Type RM Length L Ch R = 1 ,6071    ,211.3,184.9,86.2
XS GIS Cut Line= 4
2254065.27786537436689.4808757412253906.60534403436909.308431351
2253752.89133898437107.6490830292253461.70337301437680.970273489
#Sta/Elev= 30
       0 2260.44    36.1 2251.16    53.9 2249.74    98.3 2249.15   123.8 2242.04
     141 2239.06   152.4 2238.22     161 2237.64   177.2  2235.1   216.7 2232.91
   221.6  2231.1   231.5  2230.5   241.4 2230.53   247.9 2233.11   251.2 2234.59
   304.1 2233.85   389.6 2234.49   422.8 2235.82   500.8 2237.45   532.6 2240.87
   546.2 2238.69   582.1 2238.88   662.8 2239.75   770.5 2242.65     983 2250.43
  1093.5 2254.05  1142.9  2256.9  1148.5 2258.24  1159.6 2263.071165.073 2263.51
#Mann= 12 ,-1,0
       0     .07       0    53.9     .06       0     141      .1       0
   152.4    .016       0     161      .1       0   216.7    .045       0
   247.9     .05       0   422.8     .06       0   500.8      .1       0
   582.1     .05       0     983     .08       0  1093.5     .07       0
#Block Obstruct= 6 ,-1
   66.08   103.5  2269.7  265.59  271.11 2254.33  320.53   344.5 2254.52
  353.16  379.46 2254.87  395.35  423.32 2255.83   441.1  477.17 2257.08
Bank Sta=216.7,247.9
XS Rating Curve= 0 ,0
Exp/Cntr(USF)=0,0
Exp/Cntr=0.5,0.3

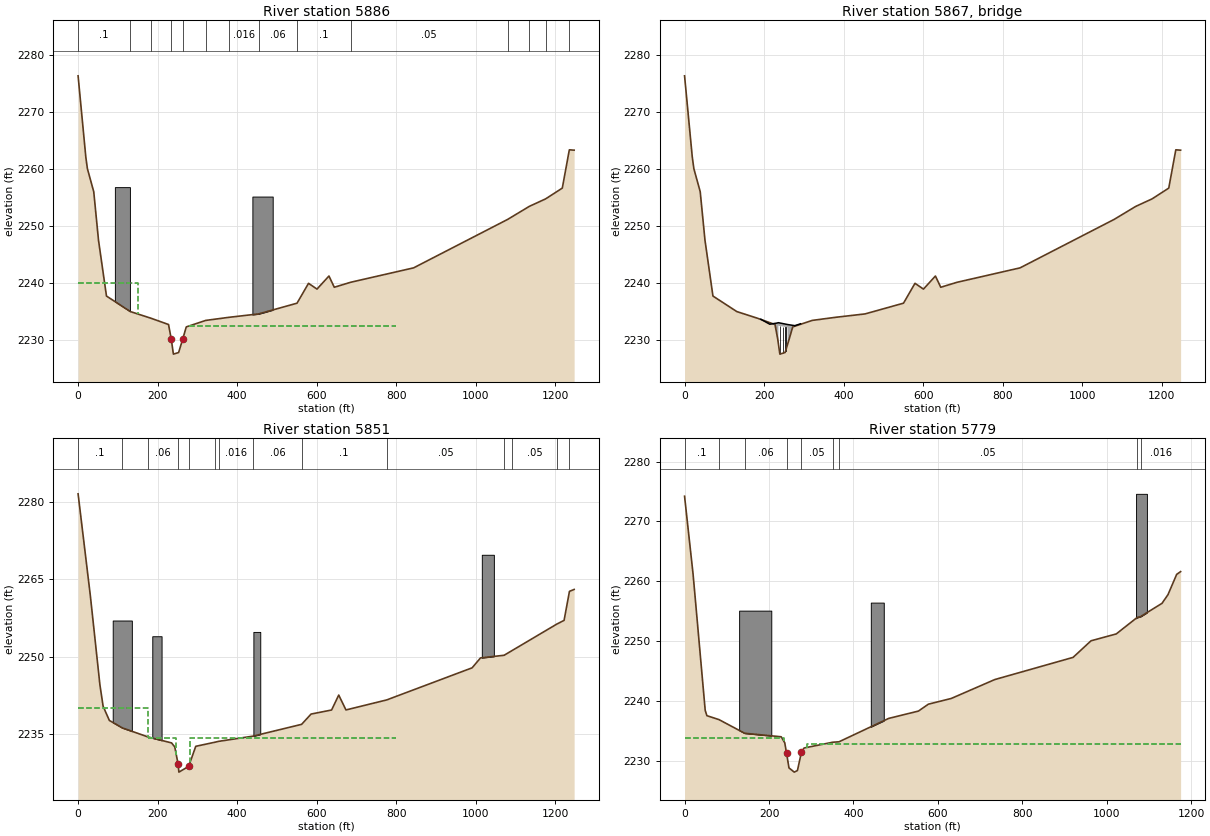
Type RM Length L Ch R = 1 ,5886    ,42.2,34.8,36.2
BEGIN DESCRIPTION:
Channel burned based on survey BRO032BU
END DESCRIPTION:
XS GIS Cut Line= 6
2253782.00084823436513.7395653062253783.77289861436737.017912497
2253792.63315048436790.1794237332253808.58160385436866.377589838
 2253715.5420345437119.4221081522253442.86103458437679.639325924
#Sta/Elev= 30
       0 2276.36    19.4 2262.14    23.4 2260.09    39.4 2256.04    51.4 2247.52
    71.4 2237.76   131.4 2235.04   183.4 2233.87   227.5 2232.77  234.34 2230.22
   239.7 2227.58  252.83 2227.86  263.02 2230.18   272.1 2232.35   321.1 2233.49
   379.3 2234.03   454.1 2234.63   550.7 2236.51   579.6 2239.99   600.9 2238.98
     631 2241.27   644.4  2239.3   685.3 2240.17   843.9  2242.7  1080.4 2251.19
    1135 2253.48  1175.9 2254.79  1217.9 2256.68  1235.6 2263.39  1247.7 2263.33
#Mann= 14 ,-1,0
       0      .1       0   131.4    .016       0   183.4     .06       0
  234.34    .045       0  263.02     .06       0   321.1     .07       0
   379.3    .016       0   454.1     .06       0   550.7      .1       0
   685.3     .05       0  1080.4     .08       0    1135     .05       0
  1175.9     .07       0  1235.6    .016       0
#XS Ineff= 3 ,-1
       0     150    2240     150     216 2232.93     279     800 2232.58
Permanent Ineff=
       F       F       F
#Block Obstruct= 2 ,-1
   92.52  130.35 2256.85  438.37  489.49  2255.2
Bank Sta=234.34,263.02
XS Rating Curve= 0 ,0
Exp/Cntr(USF)=0,0
Exp/Cntr=0.5,0.3

Type RM Length L Ch R = 3 ,5867    ,,,
BEGIN DESCRIPTION:
Unnamed Road
Survey ID: BRO030RP
END DESCRIPTION:
Bridge Culvert--1,0,-1,-1, 0
Deck Dist Width WeirC Skew NumUp NumDn MinLoCord MaxHiCord MaxSubmerge Is_Ogee
20.12536,10,2.6,0, 7, 9, , , 0.98, 0, 0,0,,
     192  214.29  231.94  236.06  259.07  277.34  291.59
 2233.69 2232.82 2233.02 2233.09 2232.77 2232.57 2232.89
                         2232.56 2232.26
     192  214.29  231.94  235.42  246.37  252.22  275.86  291.59     300
 2233.69 2232.82 2233.02    2233 2232.74 2232.96  2232.9 2232.89 2232.89
                                         2232.39 2232.39
Pier Skew, UpSta & Num, DnSta & Num=  ,240.87, 2 ,257.16, 2 , 0 , 0 , 0 ,,
      .7      .7
       0  2232.6
      .7      .7
       0  2232.6
Pier Skew, UpSta & Num, DnSta & Num=  ,247.62, 2 ,264.48, 2 , 0 , 0 , 0 ,,
      .7      .7
       0  2232.6
      .7      .7
       0  2232.6
Pier Skew, UpSta & Num, DnSta & Num=  ,253.95, 2 ,270.68, 2 , 0 , 0 , 0 ,,
      .7      .7
       0  2232.6
      .7      .7
       0  2232.6
BR Coef=-1 ,-1 , 0 ,1.25, 0 ,,,0.8,0,2,0,
WSPro=,,,, 1 ,,,, 0 ,,,, 0 ,,,,-1 ,-1 ,-1 , 0 , 0 , 0 , 0 , 0
BC Design=,, 0 ,, 0 ,,,,,,
BC Use User HTab Curves=0
BC User HTab FreeFlow(D)= 0

Type RM Length L Ch R = 1 ,5851    ,56.3,72.1,141.7
BEGIN DESCRIPTION:
Channel burned based on survey BRO028BD
END DESCRIPTION:
XS GIS Cut Line= 6
2253753.64804224436494.2470111862253750.10394149436737.017912497
2253773.14059636436852.2011868422253753.64804224436947.891907067
2253693.66486938437119.4221081522253408.36074519437655.574444295
#Sta/Elev= 30
       0 2281.65    30.9 2261.78    54.9 2244.49    62.9 2240.35    78.6 2237.59
   110.9 2236.15     175  2234.4     235 2233.22     243 2232.44  251.46  2229.1
  253.39 2227.54  277.99 2228.66   295.8 2232.56   343.5 2233.35   353.1 2233.52
   439.9 2234.54   561.9 2236.83   585.7 2238.83   637.3 2239.62   655.2 2242.52
   673.4 2239.63   775.9 2241.58   990.5 2247.82  1011.7 2249.75  1070.9 2250.26
  1090.2 2251.14    1204 2256.35  1221.7 2257.04  1235.2 2262.69    1247 2263.06
#Mann= 14 ,-1,0
       0      .1       0   110.9    .016       0     175     .06       0
  251.46    .045       0  277.99     .06       0   343.5     .05       0
   353.1    .016       0   439.9     .06       0   561.9      .1       0
   775.9     .05       0  1070.9     .06       0  1090.2     .05       0
    1204     .07       0  1235.2    .016       0
#XS Ineff= 3 ,-1
       0     175    2240     175   247.2  2234.1  280.86     800  2234.1
Permanent Ineff=
       F       F       F
#Block Obstruct= 4 ,-1
   87.03  135.13 2257.02  186.48  209.87 2253.96  440.65  457.94  2254.8
 1014.86 1045.18  2269.8
Bank Sta=251.46,277.99
XS Rating Curve= 0 ,0
Exp/Cntr(USF)=0,0
Exp/Cntr=0.5,0.3

Type RM Length L Ch R = 1 ,5779    ,23.3,29.7,31.9
BEGIN DESCRIPTION:
Channel burned based on survey  BRO022BU
END DESCRIPTION:
XS GIS Cut Line= 4
 2253741.5229631436497.418296036  2253692.459252436725.019400333
2253672.01603904436779.5346348952253242.02619167437551.646839084
#Sta/Elev= 30
       0 2274.21    20.2 2261.17    48.9  2238.4    52.9 2237.51    81.6 2236.85
   142.3 2234.57   228.9 2233.98   237.3 2232.98   241.5 2231.26  247.34 2228.77
  259.91 2228.07  267.35 2228.34   276.7 2231.38   282.9  2232.1     351 2233.07
   365.7 2233.14   483.3 2237.05   553.9 2238.28   577.4 2239.43   631.7 2240.39
   734.7 2243.55   920.2 2247.26   962.6 2250.03  1022.4 2251.18  1071.3  2253.9
  1080.4  2254.1  1130.8  2256.3    1145 2257.76  1165.5 2261.141174.821  2261.6
#Mann= 9 ,-1,0
       0      .1       0    81.6    .016       0   142.3     .06       0
   241.5    .045       0   276.7     .05       0     351    .016       0
   365.7     .05       0  1071.3     .06       0  1080.4    .016       0
#XS Ineff= 2 , 0
           234.6 2233.86   288.9         2232.78
Permanent Ineff=
       F       F
#Block Obstruct= 3 ,-1
  129.25   205.4 2255.08  441.09  471.81 2256.42 1069.32 1094.99 2274.61
Bank Sta=241.5,276.7
XS Rating Curve= 0 ,0
Exp/Cntr(USF)=0,0
Exp/Cntr=0.5,0.3