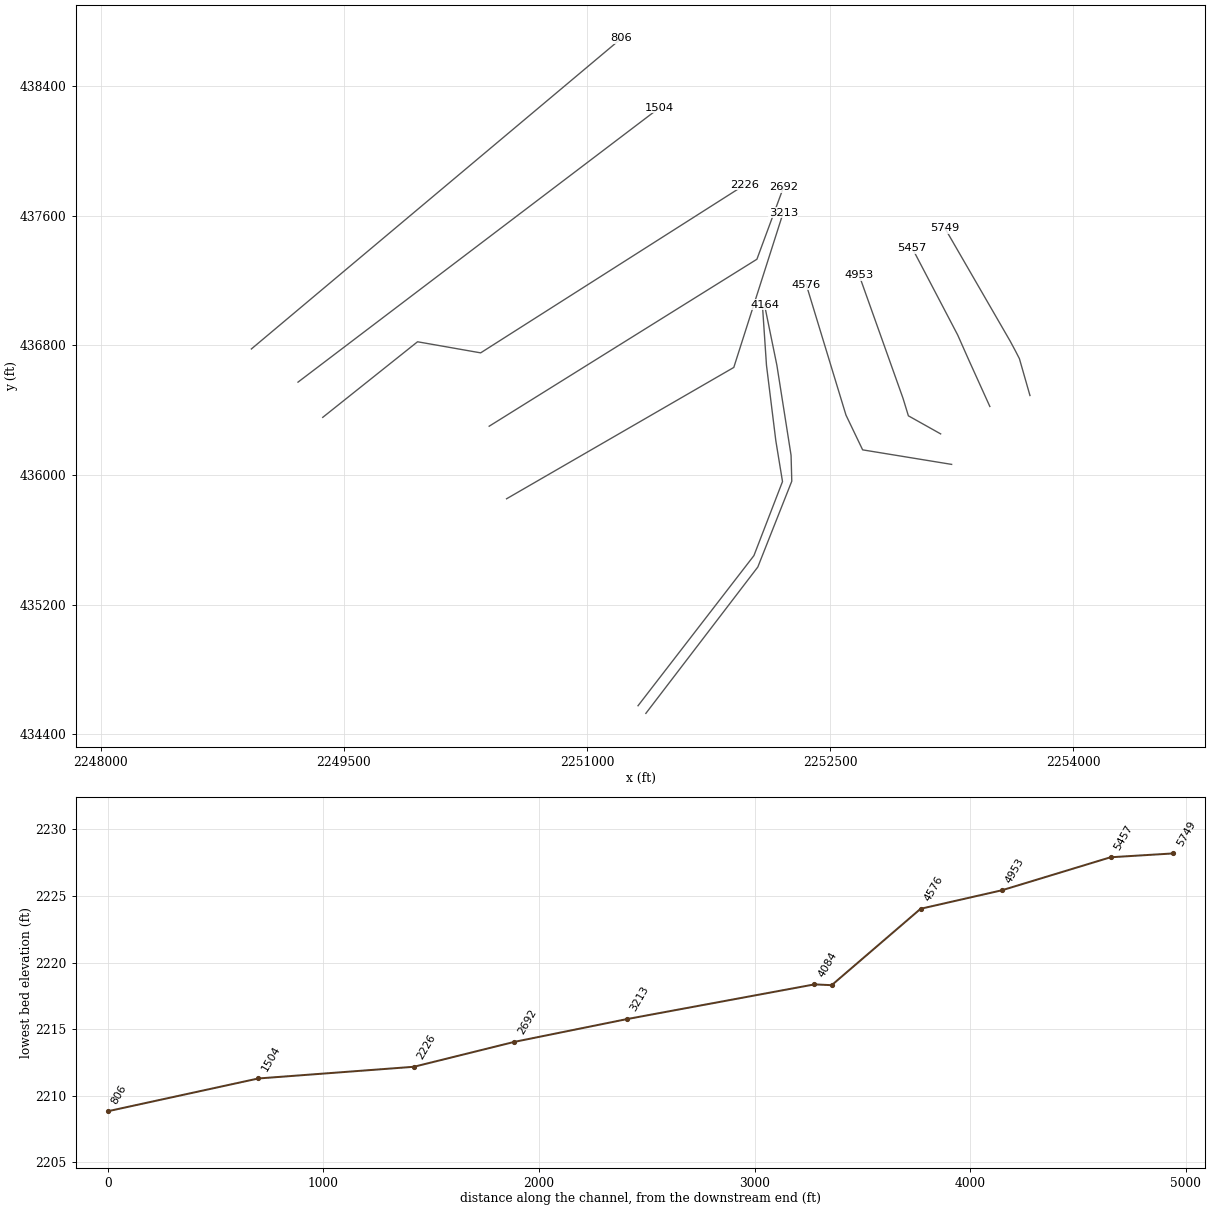
HEC-RAS study BRWNSCK.prj: BRWNSCK

--- BRWNSCK.g01 (geometry) --- (continued)

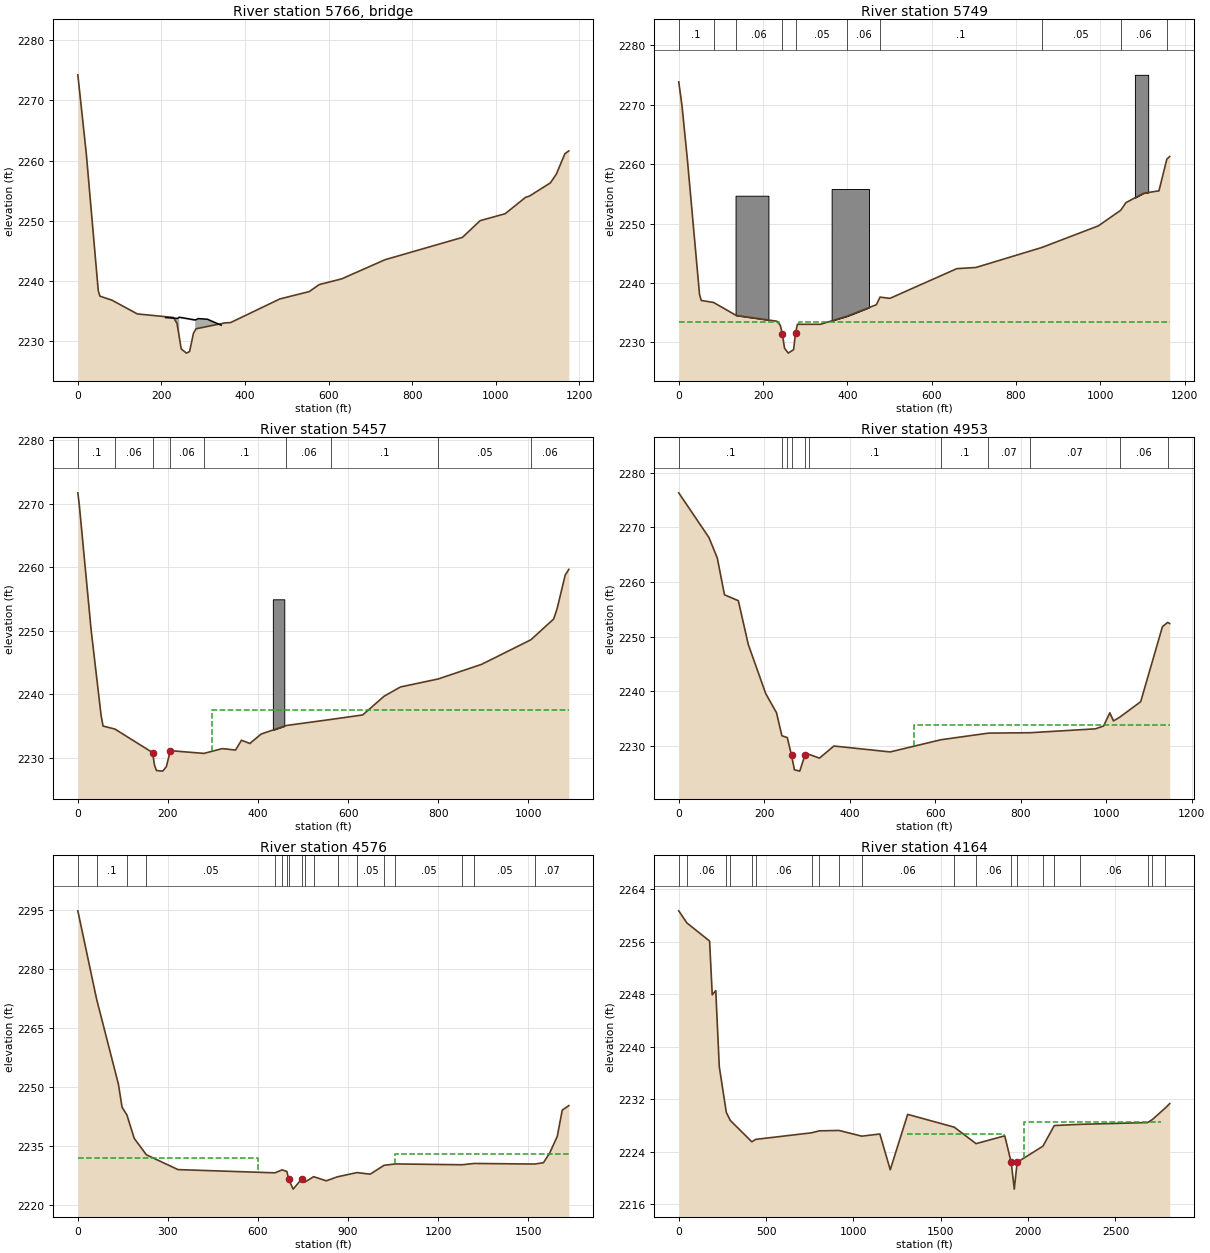
Type RM Length L Ch R = 3 ,5766    ,,,
BEGIN DESCRIPTION:
Unnamed Road
Survey ID: BRO020RP
END DESCRIPTION:
Bridge Culvert--1,0,-1,-1, 0
Deck Dist Width WeirC Skew NumUp NumDn MinLoCord MaxHiCord MaxSubmerge Is_Ogee
7.305686,13,2.6,0, 8, 9, , , 0.98, 0, 0,0,,
     210  224.03   238.2  242.66  280.92  288.43  309.96     343
 2233.97 2233.89 2233.82 2234.03 2233.57  2233.8 2233.69  2232.7
                         2233.84 2233.38
     180     210  224.03   238.2  242.66  280.92  288.43  309.96     343
 2233.97 2233.97 2233.89 2233.82 2234.03 2233.57  2233.8 2233.69  2232.7
                                 2233.84 2233.38
BR Coef=-1 ,-1 , 0 ,, 0 ,,,0.8,0,1.2,0,
WSPro=,,,, 1 ,,,, 0 ,,,, 0 ,,,,-1 ,-1 ,-1 , 0 , 0 , 0 , 0 , 0
BR U #Sta/Elev= 30
       0 2274.21    20.2 2261.17    48.9  2238.4    52.9 2237.51    81.6 2236.85
   142.3 2234.57   228.9 2233.98   237.3 2232.98   241.5 2231.26  247.34 2228.77
  259.91 2228.07  267.35 2228.34   276.7 2231.38   282.9  2232.1     351 2233.07
   365.7 2233.14   483.3 2237.05   553.9 2238.28   577.4 2239.43   631.7 2240.39
   734.7 2243.55   920.2 2247.26   962.6 2250.03  1022.4 2251.18  1071.3  2253.9
  1080.4  2254.1  1130.8  2256.3    1145 2257.76  1165.5 2261.141174.821  2261.6
BR U #Mann= 9
       0      .1    81.6    .016   142.3     .06   241.5     .04   276.7     .05
     351    .016   365.7     .05  1071.3     .06  1080.4    .016
BR D #Sta/Elev= 30
       0 2273.87     7.7 2269.88    20.2 2261.05    49.3 2238.11    53.4 2237.07
    82.6 2236.73   136.7 2234.53   228.2 2233.68   242.1 2232.58     251 2229.03
   259.9  2228.2   272.5 2228.79   279.2  2232.5   281.5 2233.05   335.9 2233.05
   400.1 2234.43   468.8 2236.35   477.6 2237.63     501 2237.42   659.6 2242.42
   705.1 2242.62   861.2 2245.98   995.3 2249.62  1048.5 2252.25  1060.8 2253.53
  1102.4 2255.11  1139.2 2255.52  1153.9 2260.33  1157.8 2260.85  1164.7  2261.3
BR D #Mann= 10
       0      .1    82.6    .016   136.7     .06   242.1     .04   279.2     .05
   400.1     .06   477.6      .1   861.2     .05  1048.5     .06  1157.8     .07
BC Design=,, 0 ,, 0 ,,,,,,
BC Use User HTab Curves=0
BC User HTab FreeFlow(D)= 0

Type RM Length L Ch R = 1 ,5749    ,277.9,291.8,287.1
BEGIN DESCRIPTION:
Channel burned based on survey 2228.2
END DESCRIPTION:
XS GIS Cut Line= 5
 2253732.7588672436489.7964888752253667.62679071436717.206789851
2253644.44418721436762.4680633462253611.32618222 436824.28833934
2253207.41730788437523.126786073
#Sta/Elev= 30
       0 2273.87     7.7 2269.88    20.2 2261.05    49.3 2238.11    53.4 2237.07
    82.6 2236.73   136.7 2234.53   232.9 2233.57     241 2232.87   245.5 2231.47
     251 2229.03   259.9  2228.2   272.5 2228.79     277 2231.58   281.5 2233.05
   335.9 2233.05   400.1 2234.43   468.8 2236.35   477.6 2237.63     501 2237.42
   659.6 2242.42   705.1 2242.62   861.2 2245.98   995.3 2249.62  1048.5 2252.25
  1060.8 2253.53  1102.4 2255.11  1139.2 2255.52  1157.8 2260.85  1164.7  2261.3
#Mann= 10 ,-1,0
       0      .1       0    82.6    .016       0   136.7     .06       0
   245.5    .045       0     277     .05       0   400.1     .06       0
   477.6      .1       0   861.2     .05       0  1048.5     .06       0
  1157.8     .07       0
#XS Ineff= 2 , 0
           237.6  2233.5   285.9          2233.5
Permanent Ineff=
       F       F
#Block Obstruct= 3 ,-1
  134.77  212.77  2254.7  362.73  451.43 2255.83 1082.14 1113.58 2275.05
Bank Sta=245.5,277
XS Rating Curve= 0 ,0
Exp/Cntr(USF)=0,0
Exp/Cntr=0.5,0.3

Type RM Length L Ch R = 1 ,5457    ,482.3,504,483.9
XS GIS Cut Line= 4
2253485.26153541436422.1847170992253356.43761741436706.513061966
2253286.74959819436863.4592762742253005.81239447437400.284092393
#Sta/Elev= 30
       0 2271.69     3.3 2269.74    29.6 2250.05    51.6  2236.7      56    2235
    82.3 2234.53   165.8 2230.83   170.2 2228.84   174.6    2228   188.5 2227.91
   196.5 2228.62   205.3 2231.13   279.9  2230.7   320.4 2231.45   350.1 2231.23
   363.2 2232.77   381.8 2232.26     407 2233.75   462.9 2235.09   562.6 2236.05
   632.3 2236.75   679.9  2239.7   716.1 2241.15     800 2242.41   896.6 2244.72
  1005.7 2248.58  1056.1 2251.84  1063.7 2253.44  1081.7 2258.74  1089.8 2259.65
#Mann= 9 ,-1,0
       0      .1       0    82.3     .06       0   165.8    .045       0
   205.3     .06       0   279.9      .1       0   462.9     .06       0
   562.6      .1       0     800     .05       0  1005.7     .06       0
#XS Ineff= 2 , 0
                          298.14         2237.56
Permanent Ineff=
       F       F
#Block Obstruct= 1 ,-1
  432.85   458.2 2254.94
Bank Sta=165.8,205.3
XS Rating Curve= 0 ,0
Exp/Cntr(USF)=0,0
Exp/Cntr=0.3,0.1

Type RM Length L Ch R = 1 ,4953    ,354.2,377.1,363.8
XS GIS Cut Line= 4
2253181.73920563 436253.086369492252982.65700306436364.659911591
2252949.84125538436471.8580206672252678.56440792437233.183366764
#Sta/Elev= 30
       0 2276.31    70.6 2268.15    90.2 2264.41     107 2257.67   139.4 2256.59
   162.8 2248.57   203.5 2239.61   228.8 2236.09   241.3 2231.89   253.9 2231.57
     264 2228.29   270.6 2225.68   283.1 2225.43   295.7 2228.46   304.3 2228.51
   329.2 2227.81     363 2230.02   494.6 2228.94   613.5 2231.17   724.6 2232.38
     822 2232.45   974.4 2233.16   993.9 2233.68  1008.4 2236.09  1016.9 2234.61
  1031.4 2235.28  1080.6 2238.12  1131.5 2251.84  1143.7 2252.621148.537 2252.41
#Mann= 11 ,-1,0
       0      .1       0   241.3    .016       0   253.9     .06       0
     264    .045       0   295.7     .06       0   304.3      .1       0
   613.5      .1       0   724.6     .07       0     822     .07       0
  1031.4     .06       0  1143.7    .016       0
#XS Ineff= 2 , 0
                          550.99         2233.87
Permanent Ineff=
       F       F
Bank Sta=264,295.7
XS Rating Curve= 0 ,0
Exp/Cntr(USF)=0,0
Exp/Cntr=0.3,0.1

Type RM Length L Ch R = 1 ,4576    ,409.3,412.5,409.7
Node Name=A
XS GIS Cut Line= 4
2253249.55841749436064.9427494782252700.44157304 436154.63912646
2252597.61889699436369.0353446142252352.59464767437174.115020946
#Sta/Elev= 30
       0 2294.72    62.2  2272.4   135.2 2250.69   147.3 2244.85   163.5 2242.88
   187.8 2236.94   228.4 2232.76   333.7    2229   656.8 2228.18   680.6 2228.93
   696.4 2228.52   702.4 2226.52   717.4 2224.04   745.5  2226.6   756.4 2225.82
   785.5  2227.2   827.8 2226.15   865.4 2227.18   930.1 2228.24   974.1 2227.84
  1020.1 2230.09  1057.7 2230.44    1280 2230.23  1321.1 2230.56  1521.8 2230.41
  1551.1 2230.74    1572 2233.22  1597.1 2237.42  1613.8  2244.11635.713 2245.25
#Mann= 18 ,-1,0
       0     .12       0    62.2      .1       0   163.5     .05       0
   228.4     .05       0   656.8     .06       0   680.6    .016       0
   696.4     .06       0   702.4    .045       0   745.5     .06       0
   756.4      .1       0   785.5     .06       0   865.4      .1       0
   930.1     .05       0  1020.1    .016       0  1057.7     .05       0
    1280    .016       0  1321.1     .05       0  1521.8     .07       0
#XS Ineff= 2 , 0
          600.34 2231.86 1056.68         2233.07
Permanent Ineff=
       F       F
Bank Sta=702.4,745.5
XS Rating Curve= 0 ,0
Exp/Cntr(USF)=0,0
Exp/Cntr=0.5,0.3

Type RM Length L Ch R = 1 ,4164    ,79.3,79.8,82.6
BEGIN DESCRIPTION:
Channel burned based on survey BRO012CU
END DESCRIPTION:
XS GIS Cut Line= 6
2251363.01725077434528.8299623792252053.81484993 435431.91801319
2252263.23861957 435961.224467872252258.86318655436120.927773229
2252171.35452608436676.6077672192252094.78444817437050.707290732
#Sta/Elev= 30
       0  2260.7    46.7 2258.86   176.7 2256.09   191.8  2247.9     212 2248.55
   232.1 2236.96   272.4 2229.99     295 2228.77   418.4 2225.51   440.5 2225.88
   760.1 2226.88   805.1 2227.18   916.9 2227.24  1047.9 2226.37  1151.3  2226.7
  1210.7 2221.25  1310.4 2229.69  1577.1 2227.74  1701.9 2225.23  1866.2 2226.42
 1903.17 2222.361920.697  2218.3  1937.1 2222.39  2084.4 2224.84  2149.9 2227.99
    2295 2228.17  2683.8 2228.44  2710.8  2228.9  2784.2 2230.64  2810.4 2231.34
#Mann= 20 ,-1,0
       0     .07       0    46.7     .06       0   272.4      .1       0
     295     .06       0   418.4     .05       0   440.5     .06       0
   760.1     .05       0   805.1     .06       0   916.9     .05       0
  1047.9     .06       0  1577.1     .05       0  1701.9     .06       0
 1903.17    .045       0  1937.1      .1       0  2084.4     .05       0
  2149.9     .07       0    2295     .06       0  2683.8     .05       0
  2710.8     .06       0  2784.2     .07       0
#XS Ineff= 3 ,-1
       0 1305.32    2229 1305.321862.731 2226.761976.731    2760  2228.5
Permanent Ineff=
       T       F       F
Bank Sta=1903.17,1937.1
XS Rating Curve= 0 ,0
Exp/Cntr(USF)=0,0
Exp/Cntr=0.5,0.3

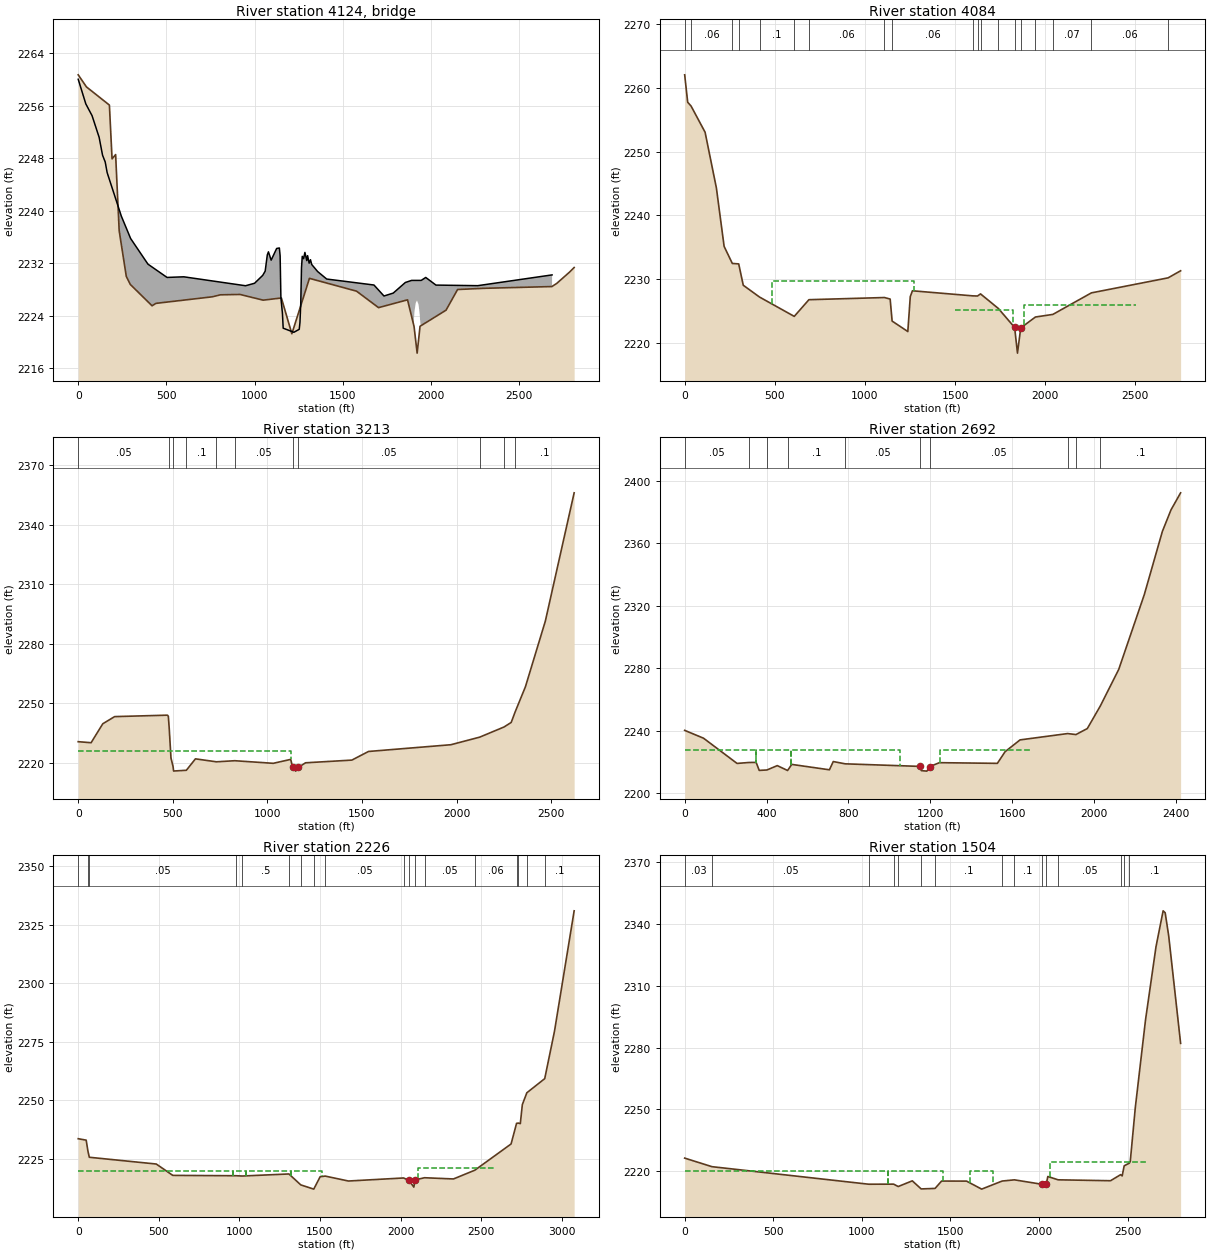
Type RM Length L Ch R = 3 ,4124    ,,,
BEGIN DESCRIPTION:
Huntersville Dr
Survey ID: BRO010RP
Arch added as per measurements in the survey
END DESCRIPTION:
Bridge Culvert--1,0,-1,-1, 0
Deck Dist Width WeirC Skew NumUp NumDn MinLoCord MaxHiCord MaxSubmerge Is_Ogee
34.24557,24,2.6,0, 60, 60, , , 0.98, 0, 0,0,,
       0  42.948  78.526 118.499 137.949 153.074 163.883 244.245  297.08 395.247
 503.513 598.269 948.371 999.2551045.6211059.4761071.5551078.0381093.2751124.615
1139.9461144.2691148.5931157.2411161.5651221.9171252.573 1256.691261.0141265.337
1269.6611277.0971284.6781295.2121299.9281308.576 1316.28 1323.081356.8011408.025
1676.0161732.6141785.0931853.719 1889.17  1897.7  1900.7  1905.7  1912.7  1919.7
  1928.7  1935.7  1940.7  1941.7  1942.7  1943.7 1969.322027.3032264.1282685.306
2260.0242256.2792254.4732251.183 2248.452247.4172245.8092239.1812235.7612231.856
2229.8322229.9292228.5672228.9452230.1512230.7932233.2742233.7342232.465 2234.25
2234.3192233.1042226.7532224.3612222.1022221.4732221.9322223.0162225.7742231.336
2233.0482232.6922233.6442232.398 2233.152232.0042232.5322231.8112230.7292229.589
2228.6772227.0052227.4462229.063 2229.38 2229.38 2229.38 2229.38 2229.38 2229.38
 2229.38 2229.38 2229.38 2229.38 2229.38 2229.38 2229.832228.6662228.5782230.219
                                                                                
                                                                                
                                                                                
                                                                                
                                 2218.332220.6632222.8382224.677 2225.95 2226.33
2225.6922224.0772221.5932220.663 2218.33
       0  42.948  78.526 118.499 137.949 153.074 163.883 244.245  297.08 395.247
 503.513 598.269 665.911 948.371 999.2551045.6211059.4761071.5551078.0381093.275
1124.6151139.9461144.2691148.5931157.2411161.5651221.9171252.573 1256.691261.014
1265.3371269.6611277.0971284.6781295.2121299.9281308.576 1316.28 1323.081356.801
1408.0251676.0161732.614 1797.44 1817.18 1825.71 1826.71 1827.71 1832.71 1839.71
 1848.71 1857.71 1864.71 1869.71 1870.71 1871.71 1897.331995.0082099.966 2661.28
2260.0242256.2792254.4732251.183 2248.452247.4172245.8092239.1812235.7612231.856
2229.8322229.9292229.2072228.5672228.9452230.1512230.7932233.2742233.7342232.465
 2234.252234.3192233.1042226.7532224.3612222.1022221.4732221.9322223.0162225.774
2231.3362233.0482232.6922233.6442232.398 2233.152232.0042232.5322231.8112230.729
2229.5892228.6772227.005 2227.71 2229.38 2229.38 2229.38 2229.38 2229.38 2229.38
 2229.38 2229.38 2229.38 2229.38 2229.38 2229.38 2229.832228.781  2228.52230.002
                                                                                
                                                                                
                                                                                
                                                                                
                                         2218.332220.6632221.5932224.0772225.692
 2226.332225.6922224.0772221.5932220.663 2218.33
BR Coef=-1 ,-1 , 0 ,, 0 ,,,0.8,0,1.2,0,
WSPro=,,,, 1 ,,,, 0 ,,,, 0 ,,,,-1 ,-1 ,-1 , 0 , 0 , 0 , 0 , 0
BC Design=,, 0 ,, 0 ,,,,,,
BC Use User HTab Curves=0
BC User HTab FreeFlow(D)= 0

Type RM Length L Ch R = 1 ,4084    ,906.6,870.8,634.4
BEGIN DESCRIPTION:
Channel burned based on survey BRO008CD
END DESCRIPTION:
XS GIS Cut Line= 6
 2251314.6711247434575.9509946982252029.73623437435502.250671181
2252206.04083549435958.9362189362252164.84169755436210.874055105
2252107.20965342 436676.046982732252082.51020593437042.422120417
#Sta/Elev= 30
       0 2262.06    16.7 2257.75    35.2 2257.17   113.2 2253.05   175.9  2244.3
   218.8 2235.12   264.3 2232.44   299.7 2232.37     325 2229.02   415.5 2227.16
   607.9 2224.13   689.2 2226.75  1108.2 2227.09  1139.8 2226.85  1150.7 2223.39
  1237.8 2221.75  1251.4 2227.23  1263.3 2228.15    1599 2227.35  1624.3 2227.33
  1641.1 2227.66    1740 2225.371830.2552222.389 1846.06 2218.361864.0732222.312
  1945.6 2224.03  2042.4 2224.44    2256 2227.82  2681.6 2230.18    2751 2231.29
#Mann= 19 ,-1,0
       0     .07       0    35.2     .06       0   264.3    .016       0
   299.7     .06       0   415.5      .1       0   607.9     .05       0
   689.2     .06       0  1108.2     .05       0  1150.7     .06       0
    1599    .016       0  1624.3     .05       0  1641.1     .05       0
    1740      .1       01830.255    .045       01864.073      .1       0
  1945.6     .06       0  2042.4     .07       0    2256     .06       0
  2681.6    .016       0
#XS Ineff= 3 ,-1
  486.76 1272.68 2229.65    15001822.031  2225.2 1882.89 2502.062225.928
Permanent Ineff=
       T       F       F
Bank Sta=1830.255,1864.073
XS Rating Curve= 0 ,0
Exp/Cntr(USF)=0,0
Exp/Cntr=0.5,0.3

Type RM Length L Ch R = 1 ,3213    ,513.8,521.6,484.4
XS GIS Cut Line= 3
2250503.59558338435852.7746339652251905.48790478 436663.09920655
2252210.51502525437618.234634311
#Sta/Elev= 30
       0  2230.6    68.1 2230.07     130 2239.64   192.6 2243.24   471.9 2243.97
   476.5 2243.41   481.2 2237.23   490.4 2222.39   501.4 2218.09   504.3 2215.81
   571.6 2216.17   619.8 2221.94   730.7 2220.45   827.7    2221    1031 2219.69
  1123.4 2221.67  1133.8 2217.64  1150.1 2215.75 1163.23  2217.6  1201.9 2219.95
  1446.8 2221.31  1534.6 2225.66  1969.9 2229.06  2122.7 2232.89  2251.3 2238.01
  2289.1  2240.3  2310.1 2245.64  2364.4 2258.32  2469.6  2291.4  2621.9 2356.09
#Mann= 11 ,-1,0
       0     .05       0   481.2      .1       0   501.4    .045       0
   571.6      .1       0   730.7     .08       0   827.7     .05       0
  1133.8    .045       0 1163.23     .05       0  2122.7    .016       0
  2251.3     .08       0  2310.1      .1       0
#XS Ineff= 2 , 0
         1122.96 2225.92
Permanent Ineff=
       F       F
Bank Sta=1133.8,1163.23
XS Rating Curve= 0 ,0
Exp/Cntr(USF)=0,0
Exp/Cntr=0.3,0.1

Type RM Length L Ch R = 1 ,2692    ,430.7,466,421.6
XS GIS Cut Line= 3
2250396.39106513436300.5096728772252048.09768767 437330.62202246
2252212.94291509437776.673814312
#Sta/Elev= 30
       0 2240.15      92 2235.13   255.8 2218.98   315.6 2219.58     349 2219.62
   364.1 2214.51   401.9 2214.78   452.3 2217.57   502.6 2214.44   522.9 2218.34
   706.9 2214.89   725.7 2220.17   784.2 2218.71    1150 2217.06  1155.9 2214.35
    1183 2214.04  1197.1 2216.98  1244.3 2219.45  1527.1 2219.02  1564.8 2226.47
  1637.9 2234.04  1870.1 2238.09  1910.8 2237.45  1966.4  2241.3  2030.4 2255.87
  2119.9 2279.19  2244.5 2326.98  2333.1 2367.58  2375.2 2381.36  2422.1 2392.25
#Mann= 10 ,-1,0
       0     .05       0   315.6      .1       0   401.9    .045       0
   502.6      .1       0   784.2     .05       0    1150    .045       0
  1197.1     .05       0  1870.1    .016       0  1910.8     .05       0
  2030.4      .1       0
#XS Ineff= 4 ,-1
       0     350 2227.64     350     520 2227.64     520 1051.46 2227.64
 1247.89 1684.51 2227.64
Permanent Ineff=
       F       T       F       F
Bank Sta=1150,1197.1
XS Rating Curve= 0 ,0
Exp/Cntr(USF)=0,0
Exp/Cntr=0.3,0.1

Type RM Length L Ch R = 1 ,2226    ,606,722.1,653.1
XS GIS Cut Line= 4
 2249369.4830166436355.0892076072249954.36574302436821.468088213
2250343.76900297436753.0594074112251975.37185204437791.218981437
#Sta/Elev= 30
       0 2233.68    49.5 2233.06    60.3  2228.4    68.9 2225.76   484.3 2222.88
   586.9 2218.03   981.3 2217.88  1017.9 2217.76  1307.6 2218.64    1381 2213.98
  1461.6 2212.17  1501.3 2217.47  1532.7 2217.73  1676.9 2215.63  2018.8 2216.93
  2052.7 2215.86  2082.6 2213.03    2090 2216.12    2149 2217.03  2328.4 2216.51
  2460.9 2220.24    2686 2231.44    2720 2240.24  2730.8 2240.34  2743.2 2240.11
  2755.9 2248.25  2783.8 2253.28  2894.7  2259.3    2955 2279.41  3077.3  2330.9
#Mann= 18 ,-1,0
       0     .03       0    60.3    .016       0    68.9     .05       0
   981.3    .045       0  1017.9      .5       0  1307.6      .1       0
    1381    .045       0  1461.6      .1       0  1532.7     .05       0
  2018.8     .08       0  2052.7    .045       0    2090     .08       0
    2149     .05       0  2460.9     .06       0    2720    .016       0
  2730.8     .07       0  2783.8     .05       0  2894.7      .1       0
#XS Ineff= 5 ,-1
       0     960    2220     960    1040    2220    1040 1319.15    2220
 1319.15 1514.37    2220 2107.89 2581.13 2221.28
Permanent Ineff=
       F       T       F       T       F
Bank Sta=2052.7,2090
XS Rating Curve= 0 ,0
Exp/Cntr(USF)=0,0
Exp/Cntr=0.3,0.1

Type RM Length L Ch R = 1 ,1504    ,484.8,697.4,527.4
XS GIS Cut Line= 2
 2249216.8561798436572.4154503972251446.70261569438264.852853181
#Sta/Elev= 30
       0 2226.35   154.2 2222.19  1039.2 2213.67  1179.1 2213.71  1205.4 2212.56
  1284.8 2215.31  1334.9 2211.39  1413.2 2211.63  1450.2 2215.21    1591 2215.18
  1676.4 2211.29  1791.9 2215.21  1861.4  2215.8 2015.39 2213.66  2041.3 2213.79
  2049.8 2217.42  2108.2 2215.81  2403.8 2215.37  2460.9 2218.32  2469.5 2217.71
  2480.9 2222.61    2510 2223.91  2515.2 2224.74  2543.7 2250.94  2601.4 2293.55
  2660.6 2329.07  2700.7 2346.44  2712.2 2345.52  2732.2 2334.26  2799.4 2282.09
#Mann= 15 ,-1,0
       0     .03       0   154.2     .05       0  1039.2      .1       0
  1179.1    .045       0  1205.4      .1       0  1334.9    .045       0
  1413.2      .1       0  1791.9     .08       0  1861.4      .1       0
 2015.39    .045       0  2041.3      .1       0  2108.2     .05       0
  2460.9     .07       0  2480.9    .016       0    2510      .1       0
#XS Ineff= 4 ,-1
       0    1150    2220    1150 1455.91    2220 1612.55 1742.62    2220
 2060.28  2606.2 2224.32
Permanent Ineff=
       F       T       T       F
Bank Sta=2015.39,2041.3
XS Rating Curve= 0 ,0
Exp/Cntr(USF)=0,0
Exp/Cntr=0.3,0.1

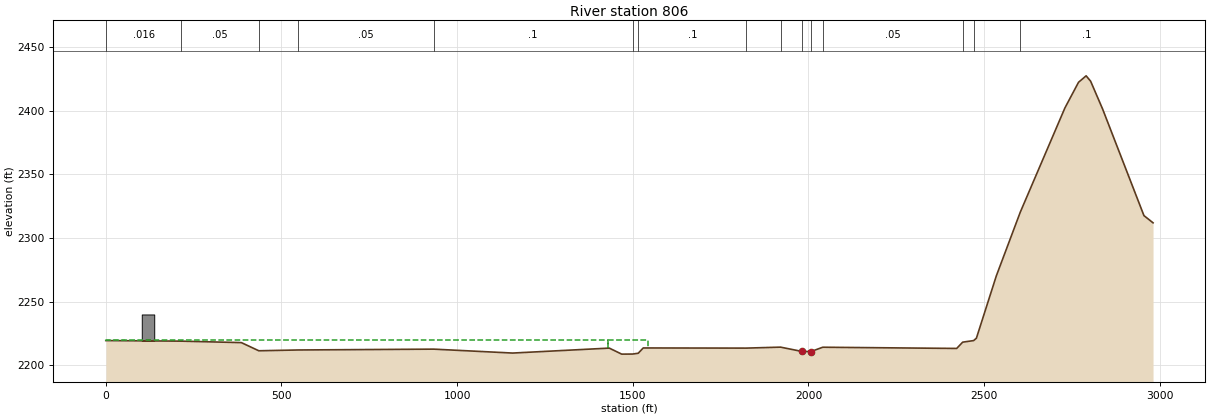
Type RM Length L Ch R = 1 ,806     ,,,
XS GIS Cut Line= 2
2248929.16266859436777.0992414762251212.24444914438693.532261048
#Sta/Elev= 30
       0 2219.49   215.1 2219.03   385.9 2217.88   435.6 2211.46   547.3 2212.09
   933.4 2212.75  1158.1 2209.67  1433.1 2213.56  1468.4 2208.83  1499.5 2208.89
  1515.5 2209.52  1529.7 2213.68    1823 2213.56  1920.6 2214.32  1982.1  2210.9
  2007.5 2210.89  2040.7 2214.25  2421.9  2213.3    2439 2218.24  2470.1 2219.47
    2478 2221.33  2534.7 2270.31  2602.9 2320.39    2730 2402.34  2768.7 2422.47
  2790.3 2427.54  2803.1 2423.34  2837.2 2401.47  2954.9 2317.692980.802 2312.02
#Mann= 15 ,-1,0
       0    .016       0   215.1     .05       0   435.6    .025       0
   547.3     .05       0   933.4      .1       0  1499.5    .045       0
  1515.5      .1       0    1823     .05       0  1920.6      .1       0
  1982.1    .045       0  2007.5      .1       0  2040.7     .05       0
    2439    .016       0  2470.1     .07       0  2602.9      .1       0
#XS Ineff= 2 ,-1
       0  1428.3    2220  1428.3 1542.13    2220
Permanent Ineff=
       F       T
#Block Obstruct= 1 ,-1
   102.4   137.9    2240
Bank Sta=1982.1,2007.5
XS Rating Curve= 0 ,0
Exp/Cntr(USF)=0,0
Exp/Cntr=0.3,0.1
LCMann Table=0

Chan Stop Cuts=-1
Use User Specified Reach Order=0
Composite Channel Slope=5